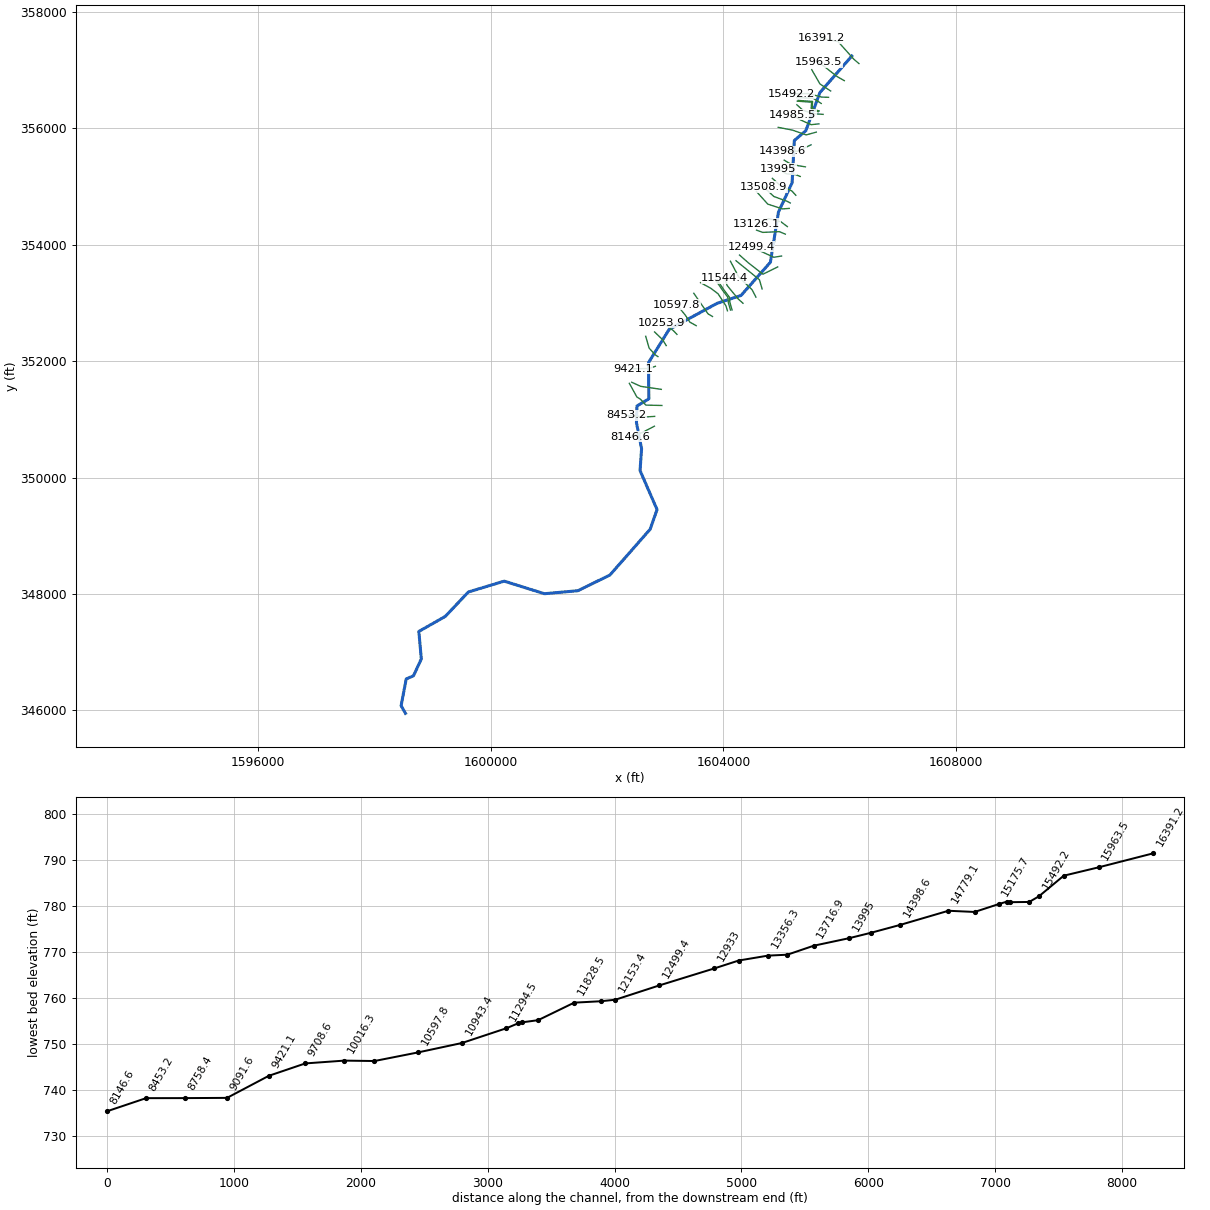
--- BIGRN.prj (project) ---

Proj Title=BIGRN
Current Plan=p01
Default Exp/Contr=0,0
English Units
Geom File=g01
Flow File=f01
Plan File=p01
BEGIN DESCRIPTION:
END DESCRIPTION:
DSS Export Rating Curves= 0
DSS Export Rating Curve Sorted= 0
DSS Export Volume Flow Curves= 0
DXF Filename=..\..\..\..\04_EngrWorking\AFG\Approximate\BIGRN\BIGRN.
DXF OffsetX= 0
DXF OffsetY= 0
DXF ScaleX= 0
DXF ScaleY= 0

--- BIGRN.p01 (plan) ---

Plan Title=Floodplain
Program Version=4.00
Geom File=g01
Flow File=f01
K Sum by GR=0
Std Step Tol=0.01
Critical Tol=0.01
Num of Std Step Trials=20
Max Error Tol=0.3
Flow Tol Ratio=0.001
Split Flow NTrial=30
Split Flow Tol=0.02
Split Flow Ratio=0.02
Log Output Level=0
Friction Slope Method=1
Unsteady Friction Slope Method=2
Unsteady Bridges Friction Slope Method=1
Global Log Level=0
CheckData=False
Run HTab=0
Run UNet=0
Run PostProcess=0
UNET Theta=0
UNET Theta Warmup=0
UNET ZTol=0
UNET ZSATol=0
UNET MxIter=0
UNET MaxInSteps=0
UNET DtIC=0
UNET DtMin=0
UNET MaxCRTS=0
UNET WFStab=0
UNET SFStab=0
UNET WFX=0
UNET SFX=0
UNET DSS MLevel=0
UNET DZMax Abort=0
UNET Convert EG Bridges=0
UNET Use Existing IB Tables=0
UNET Froude Limit=0
UNET Froude Power=0
Write IC File=0
Echo Input=False
Echo Output=False
Write Detailed=0

--- BIGRN.f01 (steady flow) ---

Flow Title=NFF Regression Equation
Program Version=4.10
Number of Profiles= 1
Profile Names=P100yr
River Rch & RM=BIGRN,Main            ,16391.2
1035.356
River Rch & RM=BIGRN,Main            ,14398.6
1075.599
River Rch & RM=BIGRN,Main            ,12499.4
1192.377
River Rch & RM=BIGRN,Main            ,11828.5
1400.745
River Rch & RM=BIGRN,Main            ,11415.8
1411.114
River Rch & RM=BIGRN,Main            ,8146.6
1559.188
River Rch & RM=BIGRN,Main            ,4451.1
1732.042
River Rch & RM=BIGRN,Main            ,585.7
1836.315
Boundary for River Rch & Prof#=BIGRN,Main            , 1
Up Type= 0
Dn Type= 3
Dn Slope=0.007
DSS Import GetInterval= 0
DSS Import GetPeak= 0
DSS Import FillOption= 0

--- BIGRN.g01 (geometry) ---

Geom Title=USGS 10m DEM
Program Version=4.10

River Reach=BIGRN           ,Main
Reach XY= 30
     1606207.723      357243.624     1605658.353      356615.152
     1605417.467      355960.204     1605219.551      355792.235
      1605181.79      355066.975     1604947.415      354563.068
     1604808.092      353699.788     1604304.186      353129.475
     1603891.426      352994.058     1603068.075      352545.708
     1602714.342      351976.046     1602719.768      351353.217
     1602515.774      351230.603     1602507.094      350941.975
     1602594.985      350496.011     1602568.943      350120.577
     1602860.827      349450.004     1602742.554      349112.548
     1602051.365      348325.873      1601500.15       348055.69
     1600923.977      348004.692     1600234.959      348220.621
     1599618.639      348033.989     1599222.588      347615.152
     1598767.945       347355.82     1598810.262      346883.815
     1598675.714      346594.102     1598550.931      346539.848
      1598463.04      346080.864     1598538.495       345948.42

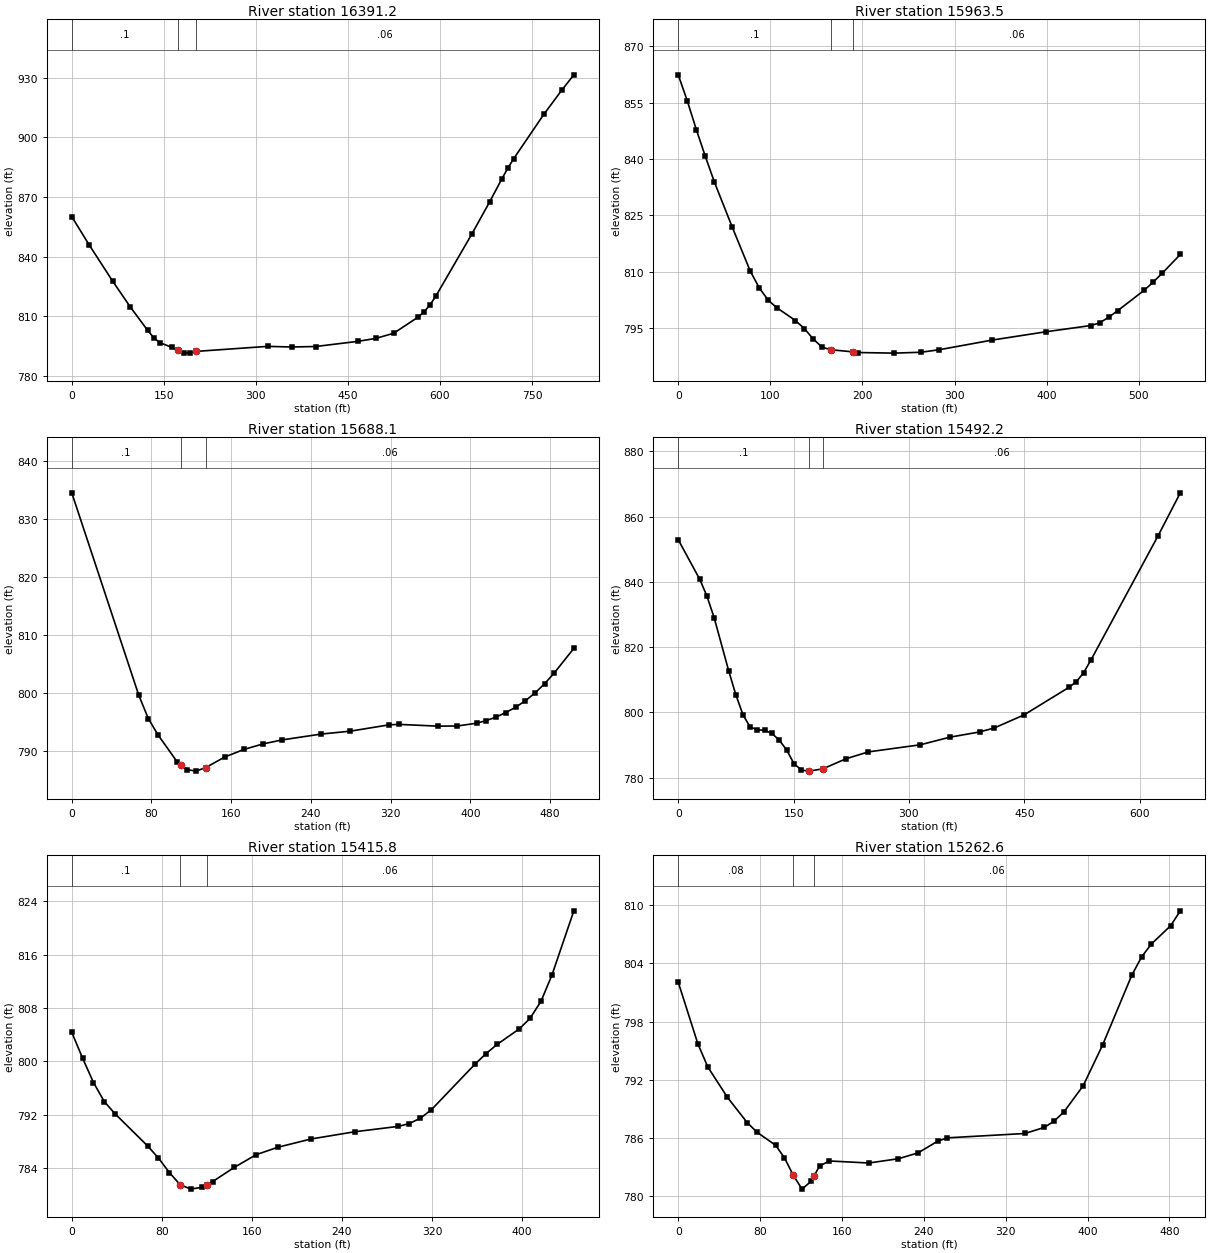
Type RM Length L Ch R = 1 ,16391.2 ,423.3,427.6,431.3
XS GIS Cut Line= 4
      1606330.27      357113.635     1606243.464       357187.42
     1605970.026      357493.409     1605681.398      357547.663
#Sta/Elev= 30
       0   860.1    28.5  845.78    66.5  827.65    94.9   814.8   123.7  802.77
   133.5  799.12   143.2  796.66   162.8  794.26   172.4  792.68   182.3  791.34
   192.1  791.49   201.9   792.2   319.1  794.74   358.2  794.43   397.3  794.67
   465.7  797.25     495  798.74   524.3  801.33   563.4  809.31   573.2  811.88
     583  815.37   592.8  819.87   651.6  851.21   680.9  867.56   700.5     879
   710.3  884.44   720.1  889.34     769  911.57   798.4  923.82     818  931.52
#Mann= 3 , 0 , 0
       0      .1       0   172.4    .045       0   201.9     .06       0
Bank Sta=172.4,201.9
XS Rating Curve= 0 ,0
Exp/Cntr=0.3,0.1

Type RM Length L Ch R = 1 ,15963.5 ,273.5,275.4,277.2
XS GIS Cut Line= 3
     1606078.533      356820.666     1605959.176      356887.941
     1605637.995      357139.677
#Sta/Elev= 30
       0  862.37     9.8  855.46    19.6  847.82    29.4  840.68    39.2  833.87
    58.7  821.81    78.3  810.08    88.1  805.63    97.9  802.34   107.6   800.3
   127.2     797     137  794.83   146.7  792.04   156.4  789.86   166.2  789.21
   189.4  788.66   195.3  788.48   234.2  788.32   263.3  788.55   282.8   789.2
     341   791.8   399.4  794.01   447.9  795.66   457.6  796.38   467.4  797.88
   477.1  799.61   506.2  805.11   515.9  807.28   525.7  809.64   545.1  814.57
#Mann= 3 , 0 , 0
       0      .1       0   166.2    .045       0   189.4     .06       0
Bank Sta=166.2,189.4
XS Rating Curve= 0 ,0
Exp/Cntr=0.3,0.1

Type RM Length L Ch R = 1 ,15688.1 ,188.7,195.9,203.1
XS GIS Cut Line= 3
     1605844.158      356642.715     1605659.697      356764.243
     1605518.638      357009.468
#Sta/Elev= 29
       0  834.49    67.2   799.6    76.8  795.57    86.4  792.78   105.6  788.14
   109.2  787.63   115.2  786.78   124.8   786.5   134.5  787.12   153.7  788.95
   172.9  790.25   192.1   791.2   211.3  791.89   250.2  792.89   279.4  793.39
   318.4  794.48   328.2  794.56   367.2  794.26   386.7  794.28   406.2  794.76
     416  795.23   425.8  795.82   435.5   796.6   445.3  797.51     455  798.62
   464.8  799.97   474.5  801.58   484.3  803.46   503.8  807.67
#Mann= 3 , 0 , 0
       0      .1       0   109.2    .045       0   134.5     .06       0
Bank Sta=109.2,134.5
XS Rating Curve= 0 ,0
Exp/Cntr=0.3,0.1

Type RM Length L Ch R = 1 ,15492.2 ,83.6,76.4,69.3
XS GIS Cut Line= 4
     1605807.266      356534.208     1605685.738      356538.548
     1605462.214      356599.312     1605162.735      356594.972
#Sta/Elev= 30
       0   852.9    28.1  840.72    37.4  835.57    46.8  828.93    65.5  812.83
    74.8  805.48    84.2  799.26    93.5  795.53   102.9  794.68   112.2  794.52
   121.6   793.6   131.3  791.53   140.9  788.52   150.6  784.26   160.2  782.36
   169.9  782.02   187.9  782.71   218.1   785.8   247.1  787.91   314.6  790.08
   353.2  792.42   391.9  794.02   411.2  795.26   449.9  799.28   507.8  807.65
   517.5  809.38   527.2   812.2   536.8  816.14   623.8  854.06   652.8  867.26
#Mann= 3 , 0 , 0
       0      .1       0   169.9    .045       0   187.9     .06       0
Bank Sta=169.9,187.9
XS Rating Curve= 0 ,0
Exp/Cntr=0.3,0.1

Type RM Length L Ch R = 1 ,15415.8 ,157.3,153.1,129.3
XS GIS Cut Line= 3
      1605681.17      356428.754     1605544.017      356518.163
     1605261.899      356529.448
#Sta/Elev= 30
       0  804.34     9.6  800.46    19.3   796.8    28.9  793.94    38.5   792.1
    67.4  787.28      77  785.47    86.7  783.29    96.3  781.46   105.9   780.8
   115.6  781.08   119.9  781.47   125.2  781.94   144.5  784.07   163.7  785.96
   183.2  787.09   212.4  788.32   251.4  789.41   290.3  790.22     300  790.65
   309.8  791.45   319.5  792.71   358.4  799.58   368.2  801.15   377.9  802.52
   397.4  804.82   407.1  806.41   416.9  808.99   426.6  812.91   446.1  822.57
#Mann= 3 , 0 , 0
       0      .1       0    96.3    .045       0   119.9     .06       0
Bank Sta=96.3,119.9
XS Rating Curve= 0 ,0
Exp/Cntr=0.3,0.1

Type RM Length L Ch R = 1 ,15262.6 ,22.1,22.1,41.7
XS GIS Cut Line= 5
     1605646.448      356299.413     1605563.115      356322.851
     1605525.354      356358.007     1605533.167      356463.476
     1605287.073      356480.837
#Sta/Elev= 30
       0  802.06    19.2  795.71    28.9  793.33    48.1   790.2    67.3  787.61
      77  786.61    95.2  785.26   103.8  783.97   112.4  782.18     121  780.75
   129.6  781.54  132.42782.0666   138.2  783.14   147.8  783.65   186.2  783.44
   215.1  783.88   234.3  784.48   253.4  785.68   262.9  786.03   338.8  786.48
   357.8  787.11   367.3  787.76   376.8  788.69   395.7   791.4   414.7   795.6
   443.2  802.78   452.7  804.65   462.2  805.98   481.1  807.87   490.6  809.41
#Mann= 3 , 0 , 0
       0     .08       0   112.4    .045       0  132.42     .06       0
Bank Sta=112.4,132.42
XS Rating Curve= 0 ,0
Exp/Cntr=0.3,0.1

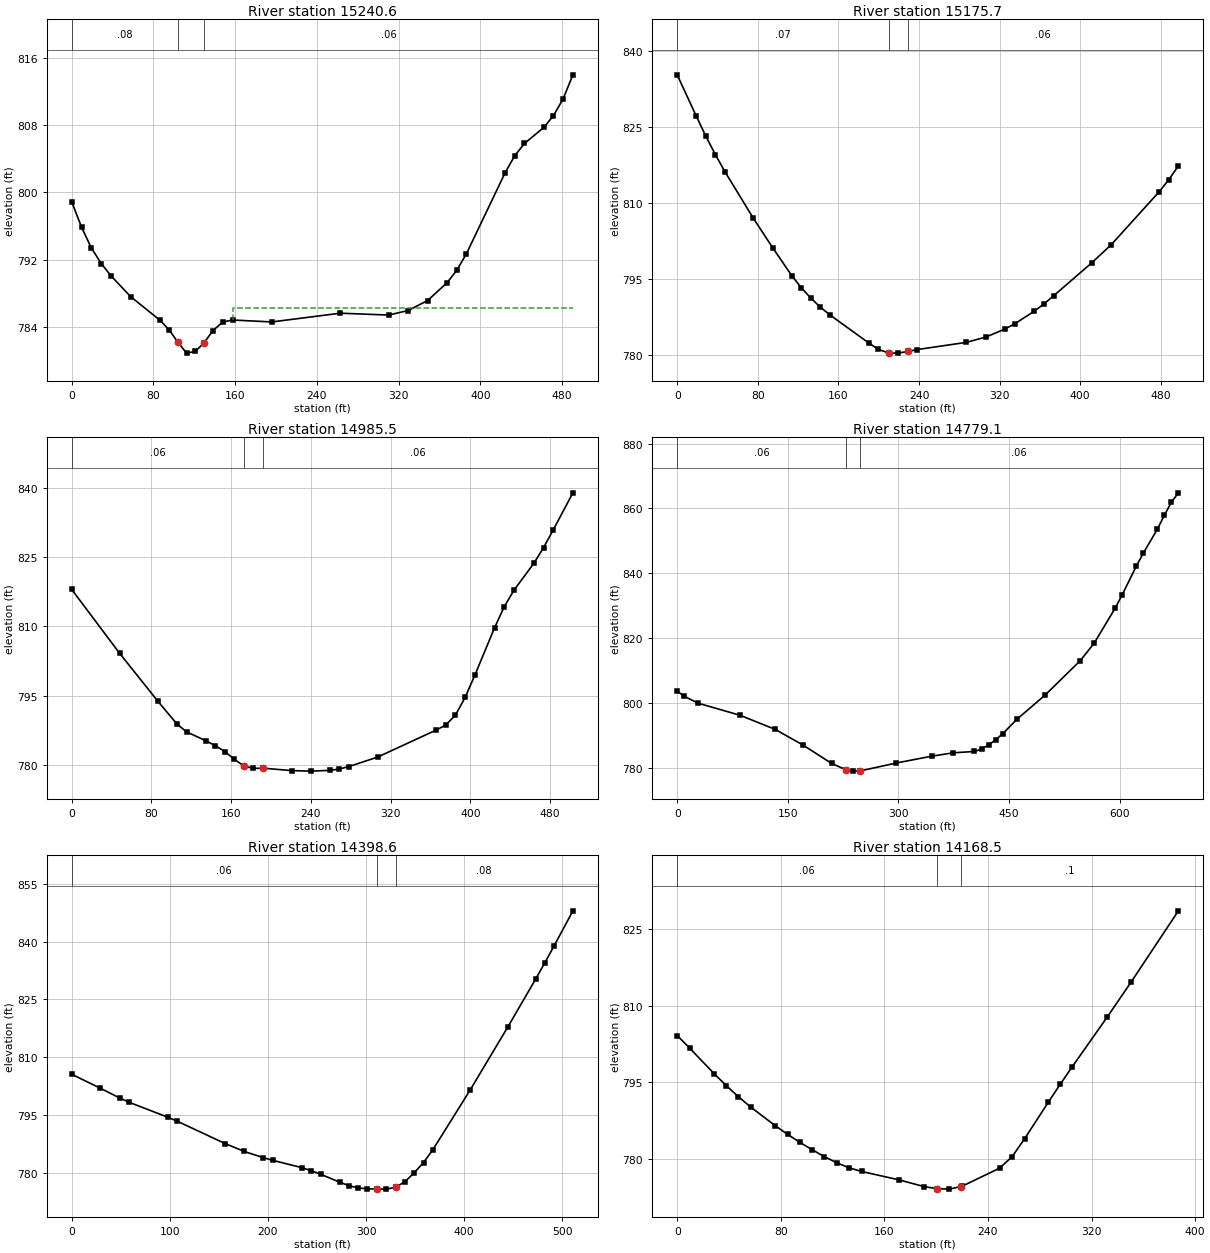
Type RM Length L Ch R = 1 ,15240.6 ,54.6,64.9,75.2
XS GIS Cut Line= 5
     1605629.955      356286.393     1605546.622       356309.83
     1605508.861      356344.986     1605516.674      356450.455
      1605270.58      356467.816
#Sta/Elev= 30
       0  798.89     9.6  795.87    19.2  793.39    28.9  791.54    38.5  790.07
    57.7   787.6    86.6  784.77    95.2  783.67   104.1  782.15   112.4  780.88
     121  781.09   129.6  782.11   138.2  783.56   147.8  784.58   157.4  784.82
   195.8  784.59   262.9  785.63   310.3  785.41   329.3  785.95   348.3  787.13
   367.3  789.24   376.8  790.72   386.2  792.66   424.2  802.33   433.7  804.37
   443.2  805.82   462.2  807.74   471.6  809.14   481.1  811.15   490.6  813.99
#Mann= 3 , 0 , 0
       0     .08       0   104.1    .045       0   129.6     .06       0
#XS Ineff= 2 , 0
                          157.78          786.28
Permanent Ineff=
       F       F
Bank Sta=104.1,129.6
XS Rating Curve= 0 ,0
Exp/Cntr=0.3,0.1

Type RM Length L Ch R = 1 ,15175.7 ,192.6,190.2,187.6
XS GIS Cut Line= 4
      1605713.95      356241.239      1605553.36       356252.09
     1605368.898      356310.684     1605262.561       356406.17
#Sta/Elev= 30
       0  835.32    18.9  827.17    28.4  823.21    37.9  819.54    47.3  816.21
    75.7  806.94    94.7  801.18   113.6  795.67   123.1  793.27   132.6  791.22
     142  789.43   151.5   787.9     190  782.36   199.7  781.08   209.8  780.37
     219  780.34   228.7  780.67   238.4  781.05   286.8  782.46   306.1   783.5
   325.5  785.12   335.2  786.16   354.5  788.64     364  790.06   373.6  791.67
   411.7  798.23   430.7  801.75   478.4  812.23   487.9  814.62   497.4  817.32
#Mann= 3 , 0 , 0
       0     .07       0   209.8    .045       0   228.7     .06       0
Bank Sta=209.8,228.7
XS Rating Curve= 0 ,0
Exp/Cntr=0.3,0.1

Type RM Length L Ch R = 1 ,14985.5 ,202.2,206.4,210.7
XS GIS Cut Line= 4
     1605642.976      356078.059     1605509.295       356064.17
     1605325.267      356145.768     1605184.642      356236.045
#Sta/Elev= 30
       0  817.95      48  804.15    86.4  793.76   105.6  788.82   115.2  787.13
   134.4  785.22     144  784.15   153.6  782.87   163.2  781.18   172.7  779.74
   182.3  779.22   191.9  779.27   220.7  778.74   239.8  778.63     259  778.79
   268.6  779.09   278.2  779.63     307  781.68   365.2  787.48     375  788.57
   384.9  790.73   394.7  794.61   404.5  799.43   424.2  809.66     434  814.26
   443.8  817.83   463.5  823.58   473.3  826.99   483.2   830.9   502.8  838.87
#Mann= 3 , 0 , 0
       0     .06       0   172.7    .045       0   191.9     .06       0
Bank Sta=172.7,191.9
XS Rating Curve= 0 ,0
Exp/Cntr=0.3,0.1

Type RM Length L Ch R = 1 ,14779.1 ,374.8,380.5,385.5
XS GIS Cut Line= 4
     1605597.197      355936.552     1605423.585      355887.941
     1605185.738      355971.274     1604942.683      356018.149
#Sta/Elev= 30
       0  803.58     9.5  802.01    28.5  799.86    85.4  796.13   132.8  791.79
   170.8  786.92   209.4  781.27   228.8  779.32   238.4  778.89   248.1  778.95
   296.6  781.37   345.1   783.5   374.2  784.54   403.2  784.96   412.9   785.7
   422.6  787.03   432.3  788.62   441.8  790.51   460.9  794.93     499  802.38
   546.6  812.98   565.6  818.42   594.2  829.28   603.7   833.4   622.7  842.18
   632.2   846.2   651.3  853.62   660.8  857.93   670.3  861.93   679.8  864.84
#Mann= 3 , 0 , 0
       0     .06       0   228.8    .045       0   248.1     .06       0
Bank Sta=228.8,248.1
XS Rating Curve= 0 ,0
Exp/Cntr=0.3,0.1

Type RM Length L Ch R = 1 ,14398.6 ,235.4,230.1,224.5
XS GIS Cut Line= 3
     1605506.919      355717.802     1605277.752      355608.427
     1605020.808      355608.427
#Sta/Elev= 30
       0  805.58    29.3  801.96    48.8  799.45    58.6  798.32    97.7  794.48
   107.4  793.44   156.3  787.64   175.8  785.59   195.3  783.98   205.1  783.27
   234.4   781.4   244.2   780.6   253.9  779.67     273  777.63   282.5  776.73
     292  776.12   301.5   775.9     311  775.84   320.6  775.82   330.2   776.3
   339.6  777.74   349.1  780.04   358.6  782.72   368.1  786.02   406.2  801.53
   444.3  817.74   472.8  830.21   482.3  834.49   491.8   838.9   510.9  847.95
#Mann= 3 , 0 , 0
       0     .06       0     311    .045       0   330.2     .08       0
Bank Sta=311,330.2
XS Rating Curve= 0 ,0
Exp/Cntr=0.3,0.1

Type RM Length L Ch R = 1 ,14168.5 ,169.7,173.5,176.7
XS GIS Cut Line= 4
     1605410.131      355339.329     1605288.603      355358.861
     1605147.544      355393.583     1605045.547      355454.347
#Sta/Elev= 29
       0  804.14     9.5  801.71    28.4  796.71    37.9  794.34    47.3  792.17
    56.8  790.15    75.8   786.5    85.2  784.82    94.7  783.27   104.2  781.82
   113.6  780.47   123.1  779.28   132.8  778.27   142.5  777.56   171.5  775.91
   190.9  774.59   200.6  774.21   210.2  774.11     219  774.61   219.9  774.66
     249  778.21   258.7  780.46   268.4  783.99   286.6  791.09   295.8   794.6
   304.9  797.96   332.3  807.81   350.6   814.6   387.1  828.52
#Mann= 3 , 0 , 0
       0     .06       0   200.6    .045       0     219      .1       0
Bank Sta=200.6,219
XS Rating Curve= 0 ,0
Exp/Cntr=0.3,0.1

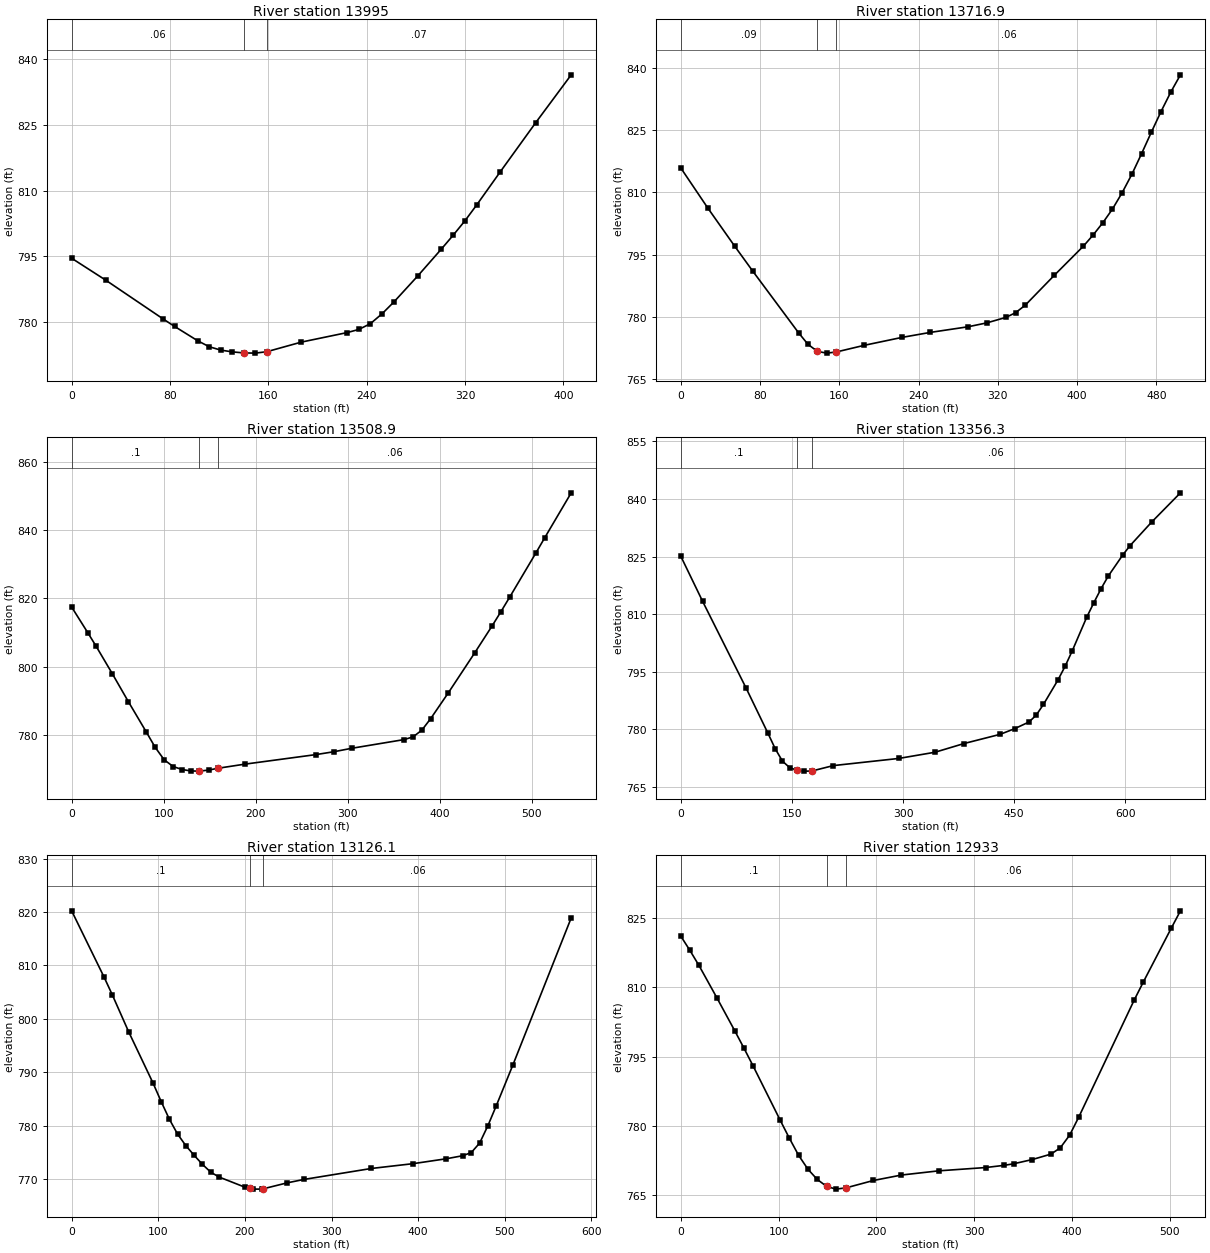
Type RM Length L Ch R = 1 ,13995   ,285.7,278.1,270.6
XS GIS Cut Line= 4
     1605321.155      355174.399      1605243.03      355204.781
      1605084.61      355219.972     1604943.551      355302.437
#Sta/Elev= 25
       0  794.57    27.9  789.54    74.5  780.71    83.8  779.01   102.6  775.74
   111.9  774.39   121.3  773.62   130.6  773.22     140  772.98   149.4  772.93
   158.7  773.25   186.8  775.44   224.2  777.62   233.6  778.33     243  779.64
   252.6  781.92   262.2  784.61   281.4  790.48   300.6  796.61   310.2  799.76
   319.9  803.09   329.5  806.72   348.7  814.29   377.5  825.48   406.4   836.4
#Mann= 3 , 0 , 0
       0     .06       0     140    .045       0   158.7     .07       0
Bank Sta=140,158.7
XS Rating Curve= 0 ,0
Exp/Cntr=0.3,0.1

Type RM Length L Ch R = 1 ,13716.9 ,205.9,208,210
XS GIS Cut Line= 4
       1605245.2      354851.048     1605177.926      354924.833
     1604980.443      355018.149     1604841.554      355141.847
#Sta/Elev= 30
       0  815.85    27.2  806.23    54.5  796.99    72.6  791.03   118.8   776.2
   128.3  773.42   137.2  771.83   137.8  771.72   147.3   771.3   156.8  771.57
   185.3  773.19   223.3  775.09   251.8  776.29   289.8  777.64   308.8  778.58
   328.1   779.9   337.8  781.02   347.6  782.83     377  790.04   406.4  797.07
   416.2  799.75     426   802.7   435.7  805.99   445.5  809.94   455.3  814.37
   465.1  819.33   474.9  824.47   484.7  829.46   494.5  834.12   504.3   838.3
#Mann= 3 , 0 , 0
       0     .09       0   137.2    .045       0   156.8     .06       0
Bank Sta=137.2,156.8
XS Rating Curve= 0 ,0
Exp/Cntr=0.3,0.1

Type RM Length L Ch R = 1 ,13508.9 ,151.9,152.6,153.3
XS GIS Cut Line= 4
      1605149.66      354718.684     1605094.972       354747.33
     1604867.108      354830.663     1604692.628      354993.424
#Sta/Elev= 30
       0  817.42    17.6  809.88    26.5  805.98    44.1  797.94    61.7  789.68
    81.2  780.79    90.8  776.32   100.6  772.67   110.3   770.7     120  769.82
   129.7   769.4   138.7  769.35   149.1  769.66   158.8  770.18   187.9  771.38
   265.5  774.19     285  775.03   304.4  776.04   361.6   778.6   371.2   779.4
   380.7  781.37   390.3  784.75   409.4  792.28     438  803.95   457.1  811.93
   466.6  816.06   476.2  820.35   504.8  833.35   514.3  837.76     543  850.88
#Mann= 3 , 0 , 0
       0      .1       0   138.7    .045       0   158.8     .06       0
Bank Sta=138.7,158.8
XS Rating Curve= 0 ,0
Exp/Cntr=0.3,0.1

Type RM Length L Ch R = 1 ,13356.3 ,228.9,230.3,231.6
XS GIS Cut Line= 4
     1605132.353      354625.354     1605015.165      354616.673
     1604763.429      354699.138     1604568.117      354916.152
#Sta/Elev= 30
       0  825.04    29.4  813.32    88.1  790.75   117.5  779.03   127.3     775
   137.1  771.75   146.9  770.06   156.8  769.38   166.6  769.15   176.4  769.16
   205.8  770.59   294.1  772.45   343.2  774.07   382.4  776.34   431.1  778.73
   450.5  780.19     470  781.94   479.7  783.72   489.5  786.52   508.9  792.82
   518.7  796.44   528.4  800.48   547.8  809.17   557.6  813.02   567.3  816.65
     577  819.93   596.5  825.39   606.2   827.8   635.4  833.94   674.4  841.58
#Mann= 3 , 0 , 0
       0      .1       0   156.8    .045       0   176.4     .06       0
Bank Sta=156.8,176.4
XS Rating Curve= 0 ,0
Exp/Cntr=0.3,0.1

Type RM Length L Ch R = 1 ,13126.1 ,186.4,193.1,199.6
XS GIS Cut Line= 4
     1605099.801      354312.854     1604986.954      354397.489
      1604778.62      354449.573     1604574.627      354364.937
#Sta/Elev= 30
       0  820.22    37.6  807.75      47  804.46    65.8  797.57      94  787.94
   103.4  784.47   112.8  781.19   122.2  778.42   131.7  776.26   141.1  774.48
   150.8  772.76   160.6  771.26   170.3  770.35   199.6  768.48   206.4  768.22
   209.4   768.1   219.2  768.09   221.4  768.16   248.4  769.25     268   769.9
     346  771.96   394.2  772.86   432.6  773.78   451.8  774.36   461.4  774.95
     471  776.72   480.6     780   490.2  783.71   509.4  791.36   576.7   818.9
#Mann= 3 , 0 , 0
       0      .1       0   206.4    .045       0   221.4     .06       0
Bank Sta=206.4,221.4
XS Rating Curve= 0 ,0
Exp/Cntr=0.3,0.1

Type RM Length L Ch R = 1 ,12933   ,444.4,433.6,422.9
XS GIS Cut Line= 4
     1605065.079      354182.645     1604963.082      354226.048
     1604676.624      354213.027     1604570.287       354252.09
#Sta/Elev= 30
       0  821.09     9.2  818.04    18.5  814.77      37   807.7    55.4  800.52
    64.7   796.8    73.9  793.01   101.6  781.27   110.8  777.45   120.4  773.69
     130  770.66   139.5  768.46   149.1  766.96   158.6  766.37   169.2  766.66
   196.9  768.24   225.6  769.42   263.8  770.33   311.6  771.04   330.7  771.52
   340.2  771.85   359.4  772.77   378.5  773.95     388   775.3   397.6  778.05
     407  781.99   463.7  807.32   473.1  811.25   501.4  822.79   510.9  826.59
#Mann= 3 , 0 , 0
       0      .1       0   149.1    .045       0   169.2     .06       0
Bank Sta=149.1,169.2
XS Rating Curve= 0 ,0
Exp/Cntr=0.3,0.1

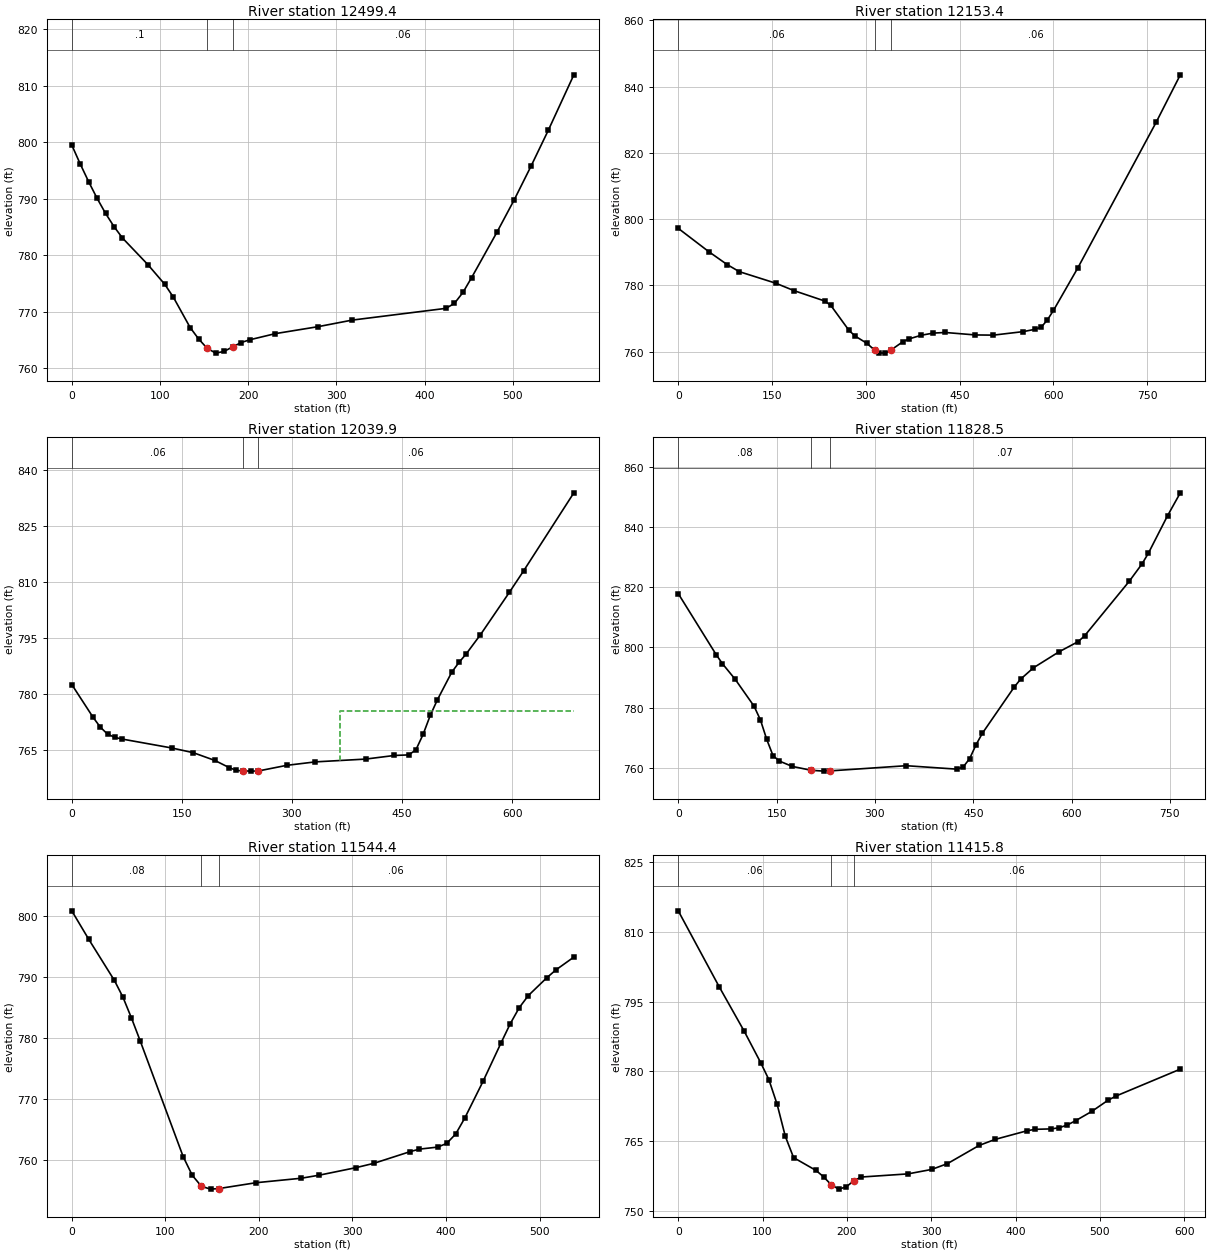
Type RM Length L Ch R = 1 ,12499.4 ,351.3,346,340.6
XS GIS Cut Line= 3
     1604999.974      353807.211     1604867.596       353785.51
     1604472.631      353967.802
#Sta/Elev= 30
       0  799.49     9.6  796.14    19.2  792.98    28.8  790.04    38.3   787.4
    47.9  785.06    57.5  783.04    86.2  778.35   105.4  774.86     115  772.62
   134.2  767.21   143.8  765.19   153.5  763.53   163.2  762.68   172.8  762.99
   182.5   763.8   192.2  764.56   201.8  765.04   230.8  766.13   279.2  767.36
   317.8  768.52   424.2   770.6   433.8  771.48   443.5  773.42   453.2  776.01
   482.2  784.12   501.5  789.77   520.8   795.8   540.2  802.09   569.2  811.91
#Mann= 3 , 0 , 0
       0      .1       0   153.5    .045       0   182.5     .06       0
Bank Sta=153.5,182.5
XS Rating Curve= 0 ,0
Exp/Cntr=0.3,0.1

Type RM Length L Ch R = 1 ,12153.4 ,113.9,113.5,113.1
XS GIS Cut Line= 4
     1604934.002      353619.711     1604680.096      353494.711
     1604430.096      353690.024     1604277.752      353824.138
#Sta/Elev= 30
       0  797.25    48.8  790.22    78.1  786.33    97.6  784.18   156.1  780.68
   185.4  778.43   234.2  775.32     244  774.01   273.2  766.43     283  764.73
   302.2  762.49   314.7  760.38   321.5  759.65   331.1  759.58   340.7  760.56
   359.9  763.09   369.5  763.89   388.8  764.98     408  765.63   427.2  765.81
   475.3  765.07   504.1  765.01   552.2  766.08   571.4   766.8     581  767.47
   590.6  769.62   600.3  772.48   638.9  785.19   764.6  829.28   803.2  843.59
#Mann= 3 , 0 , 0
       0     .06       0   314.7    .045       0   340.7     .06       0
Bank Sta=314.7,340.7
XS Rating Curve= 0 ,0
Exp/Cntr=0.3,0.1

Type RM Length L Ch R = 1 ,12039.9 ,213.4,211.4,209.1
XS GIS Cut Line= 3
     1604666.587       353240.82     1604619.712      353399.674
     1604217.368      353726.497
#Sta/Elev= 30
       0  782.47    29.2  773.63      39  771.02    48.7  769.18    58.5  768.31
    68.2  767.86   136.4  765.45   165.6  764.19     195  762.11   214.5  760.19
   224.3  759.44   233.2  759.32   243.9  759.25   253.6  759.27   292.8   760.8
   331.9  761.73   400.4  762.48   439.5  763.45     459   763.6   468.8  764.95
   478.6  769.08   488.4   774.2   498.2  778.41   517.7  785.78   527.5  788.39
   537.3  790.66   556.8  795.83     596  807.14   615.5  812.92     684  833.86
#Mann= 3 , 0 , 0
       0     .06       0   233.2    .045       0   253.6     .06       0
#XS Ineff= 2 , 0
                          365.37           775.5
Permanent Ineff=
       F       F
Bank Sta=233.2,253.6
XS Rating Curve= 0 ,0
Exp/Cntr=0.3,0.1

Type RM Length L Ch R = 1 ,11828.5 ,286.5,284.1,282
XS GIS Cut Line= 4
     1604560.304      353100.614      1604493.03      353228.652
     1604262.995      353450.007     1604121.936      353716.934
#Sta/Elev= 30
       0  817.87    57.8  797.62    67.5  794.57    86.8  789.44   115.7  780.48
   125.4  775.92     135  769.45   144.6  764.08   154.3  762.28   173.7  760.52
   202.7  759.22     222  758.94   231.7  759.02   347.8  760.74   425.2  759.59
   434.8  760.36   444.5   763.1   454.2  767.68   463.9  771.51   512.6  786.88
   522.3  789.48   541.8  793.24   580.7  798.53     610  801.92   619.7  803.82
   687.9  821.95   707.4  827.72   717.1  831.27   746.3   843.7   765.8  851.31
#Mann= 3 , 0 , 0
       0     .08       0   202.7    .045       0   231.7     .07       0
Bank Sta=202.7,231.7
XS Rating Curve= 0 ,0
Exp/Cntr=0.3,0.1

Type RM Length L Ch R = 1 ,11544.4 ,142.3,128.5,114.8
XS GIS Cut Line= 4
     1604337.539      352995.579     1604255.942      353068.496
      1604064.97      353301.135     1604025.039      353420.927
#Sta/Elev= 30
       0  800.85    18.2  796.16    45.6  789.41    54.7  786.67    63.8  783.25
      73  779.55   119.1  760.47   128.8  757.41   138.6   755.6   148.3  755.14
   157.1  755.23   196.8  756.19   245.4  756.93   264.8  757.44   303.6  758.66
     323  759.38   361.9  761.31   371.6  761.71     391  762.04   400.7  762.64
   410.4  764.19   420.1  766.81   439.6  772.83     459   779.2   468.7   782.3
   478.4  784.96   488.1  786.94   507.6  789.83   517.3  791.12   536.7  793.25
#Mann= 3 , 0 , 0
       0     .08       0   138.6    .045       0   157.1     .06       0
Bank Sta=138.6,157.1
XS Rating Curve= 0 ,0
Exp/Cntr=0.3,0.1

Type RM Length L Ch R = 1 ,11415.8 ,27.8,27.7,27.8
XS GIS Cut Line= 5
     1604149.605      352880.562     1604111.845      353012.073
     1604104.033      353100.614     1604019.397      353212.593
     1603889.189      353401.395
#Sta/Elev= 30
       0  814.54    48.9  798.09    78.2  788.65    97.7   781.9   107.5  778.22
   117.3  772.89     127  766.01   136.8  761.44   163.5  758.67   172.4   757.3
   181.3  755.63   190.2  754.66     199  755.12   207.9  756.41   216.8  757.26
   272.5  757.94   300.6   758.9   319.3  760.15   356.7  764.05   375.6  765.35
   413.9  767.23   423.4  767.53   442.5  767.62   452.1  767.88   461.6  768.48
   471.2  769.38   490.3  771.37   509.4  773.75     519  774.68   595.4  780.48
#Mann= 3 , 0 , 0
       0     .06       0   181.3    .045       0   207.9     .06       0
Bank Sta=181.3,207.9
XS Rating Curve= 0 ,0
Exp/Cntr=0.3,0.1

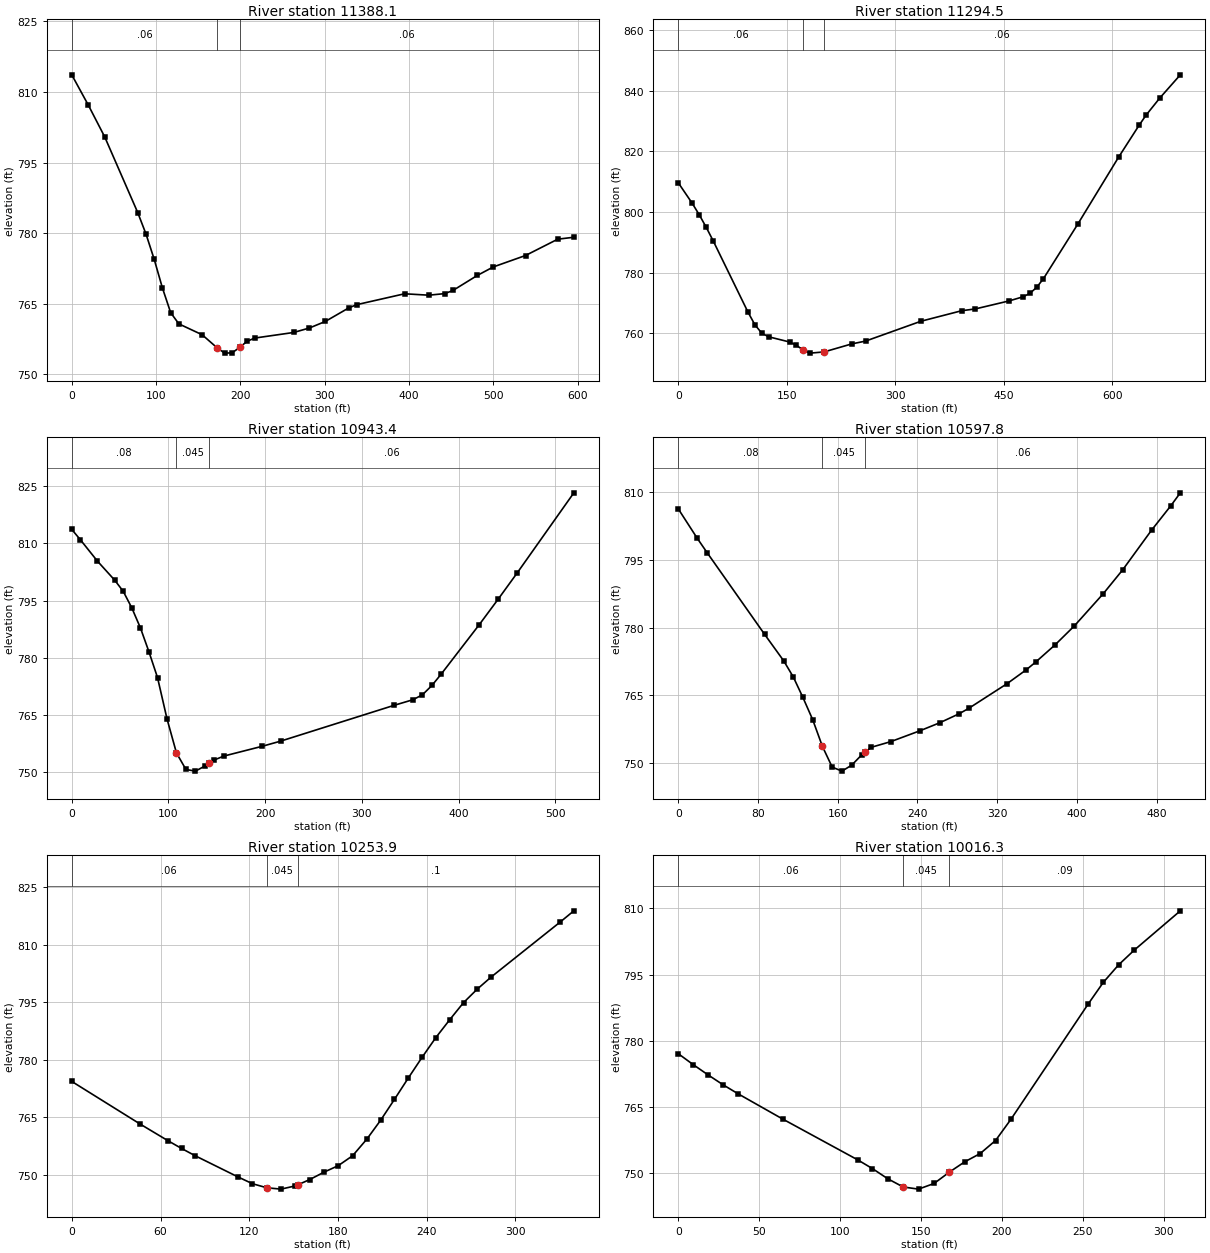
Type RM Length L Ch R = 1 ,11388.1 ,82.2,93.6,104.7
XS GIS Cut Line= 5
     1604122.262       352879.26     1604084.501       353010.77
     1604076.689      353099.312     1603992.053      353211.291
     1603861.845      353400.093
#Sta/Elev= 30
       0  813.65    19.6  807.22    39.1  800.44    78.2  784.37      88  779.81
    97.7  774.45   107.5  768.33   117.3  763.07     127  760.69   154.6  758.38
   172.4  755.59   181.3  754.47   190.2  754.53     199  755.68   207.9  756.98
   216.8  757.67   263.1  758.86   281.9  759.82   300.6   761.2   328.6   764.1
     338  764.78   394.7  767.09   423.4  766.79   442.5  767.13   452.1   767.8
   480.8  770.98   499.9   772.8   538.1  775.23   576.3   778.7   595.4  779.11
#Mann= 3 , 0 , 0
       0     .06       0   172.4    .045       0     199     .06       0
Bank Sta=172.4,199
XS Rating Curve= 0 ,0
Exp/Cntr=0.3,0.1

Type RM Length L Ch R = 1 ,11294.5 ,351,351.1,351.5
XS GIS Cut Line= 5
     1604070.178      352866.239     1604045.439      352949.573
     1603910.022      353157.906     1603782.418       353254.26
     1603607.939      353349.312
#Sta/Elev= 30
       0  809.64    19.3  802.86      29  799.08    38.6  794.96    48.3  790.46
    96.5  766.88     106  762.74   115.6  759.94   125.2  758.77   153.8  757.07
   163.4  755.98   172.9  754.35   182.5  753.39   201.6  753.79   239.8  756.43
     259  757.37   335.4  763.91   391.8  767.39   410.6  767.98   457.7  770.65
   476.5  771.98   485.9  773.09   495.3  775.06   504.8  777.96   552.1  795.91
   608.8  818.12   637.2  828.67   646.7  831.96   665.6  837.59     694  845.26
#Mann= 3 , 0 , 0
       0     .06       0   172.9    .045       0   201.6     .06       0
Bank Sta=172.9,201.6
XS Rating Curve= 0 ,0
Exp/Cntr=0.3,0.1

Type RM Length L Ch R = 1 ,10943.4 ,345.8,345.6,345.1
XS GIS Cut Line= 3
     1603813.234      352768.149     1603736.845      352813.288
     1603492.053      353167.454
#Sta/Elev= 28
       0  813.68     8.9  810.97    26.6  805.34    44.4  800.35    53.2  797.43
    62.1  793.07      71  787.82    79.9  781.48    88.7  774.75    98.5  763.92
   108.3  754.94   118.1  750.61   127.9  750.18   137.6  751.51   141.9  752.21
   147.4  753.11   157.2  754.13   196.4  756.67   215.9  758.05   333.4  767.47
   352.9  768.94   362.7  770.24   372.5  772.68   382.3  775.74   421.4  788.64
     441  795.35   460.6  802.22   519.3   823.3
#Mann= 3 , 0 , 0
       0     .08       0   108.3    .045       0   141.9     .06       0
Bank Sta=108.3,141.9
XS Rating Curve= 0 ,0
Exp/Cntr=0.3,0.1

Type RM Length L Ch R = 1 ,10597.8 ,335.7,343.9,351.6
XS GIS Cut Line= 4
      1603533.72      352610.163     1603424.345      352670.927
     1603344.484      352794.191     1603196.914       352973.01
#Sta/Elev= 30
       0  806.34    19.2  799.76    28.9  796.64    86.6  778.51   105.9  772.59
   115.5  769.01   125.1  764.49   134.9  759.57   144.7  753.61   154.5  749.03
   164.3  748.14   174.1  749.47   183.9   751.7   187.9  752.41   193.7  753.43
   213.2  754.68   242.6   757.1   262.2  758.85   281.6  760.84   291.3  762.04
     330  767.55   349.3  770.64   358.9  772.38   378.3  776.19   397.6  780.39
   426.6  787.54   445.9  792.78   474.9  801.59   494.2     807   503.8  809.89
#Mann= 3 , 0 , 0
       0     .08       0   144.7    .045       0   187.9     .06       0
Bank Sta=144.7,187.9
XS Rating Curve= 0 ,0
Exp/Cntr=0.3,0.1

Type RM Length L Ch R = 1 ,10253.9 ,240.4,237.6,235
XS GIS Cut Line= 4
     1603202.123      352460.857     1603144.831      352521.621
     1603054.553      352594.538     1602933.026      352663.982
#Sta/Elev= 27
       0  774.34    46.4  763.19      65   758.9    74.2  756.88    83.5  754.96
   112.5  749.43   122.2  747.68   131.9  746.62   141.5  746.27   151.2  747.12
   152.8  747.39   160.9  748.76   170.6   750.7   180.2  752.39   189.9  754.97
   199.6  759.34   208.9  764.25   218.2  769.67   227.6  775.26   236.9  780.64
   246.2  785.78   255.6  790.44   264.9  794.88   274.2  798.41   283.5  801.53
   330.2  815.87   339.5  818.81
#Mann= 3 , 0 , 0
       0     .06       0   131.9    .045       0   152.8      .1       0
Bank Sta=131.9,152.8
XS Rating Curve= 0 ,0
Exp/Cntr=0.3,0.1

Type RM Length L Ch R = 1 ,10016.3 ,309.5,307.7,305.7
XS GIS Cut Line= 3
     1603018.095      352268.149     1602955.595      352370.579
     1602818.442      352502.524
#Sta/Elev= 22
       0  777.07     9.2   774.6    18.5  772.24    27.7  770.02    36.9  767.99
    64.6  762.24   110.8  753.02     120  751.02   129.5  748.71     139  746.85
   148.5  746.36   158.1  747.64   167.6  750.22   177.1  752.56   186.6  754.42
   196.1  757.38   205.6  762.18   253.2  788.24   262.7  793.23   272.2  797.22
   281.8  800.53   310.3  809.45
#Mann= 3 , 0 , 0
       0     .06       0     139    .045       0   167.6     .09       0
Bank Sta=139,167.6
XS Rating Curve= 0 ,0
Exp/Cntr=0.3,0.1

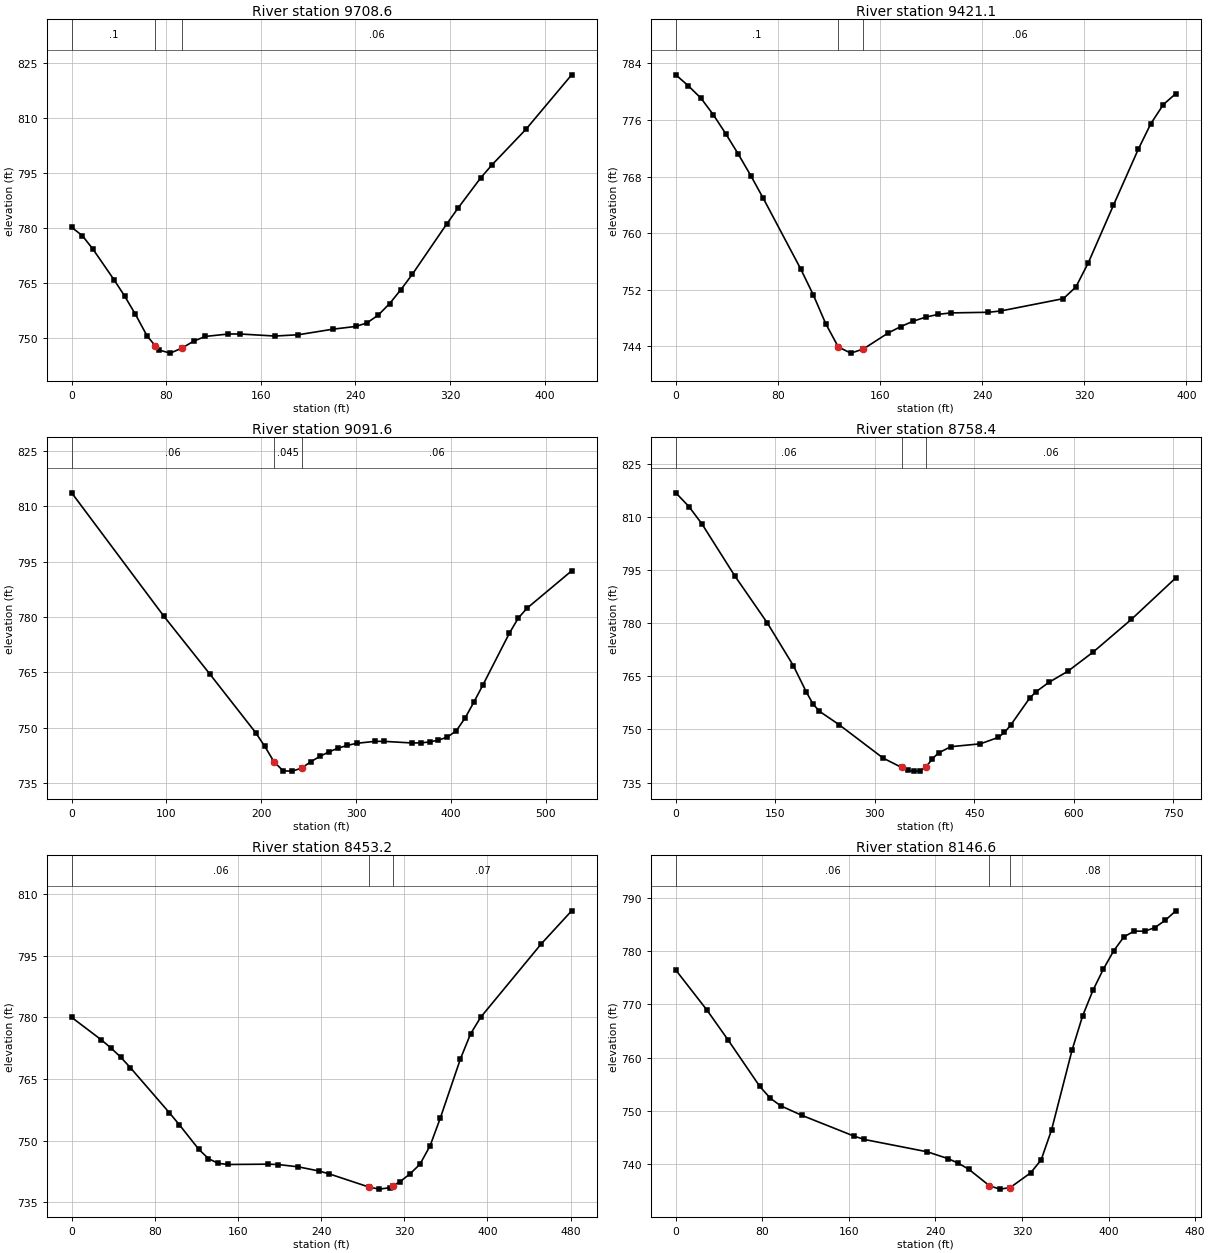
Type RM Length L Ch R = 1 ,9708.6  ,267.4,287.5,306.7
XS GIS Cut Line= 4
     1602875.734      352078.913     1602830.595      352108.427
     1602724.692      352224.746     1602665.664      352427.871
#Sta/Elev= 30
       0  780.14       9  777.86      18  774.17      36  765.72    44.9  761.29
    53.9  756.37    63.8  750.43    70.6  747.79    73.6  746.62    83.4  745.75
    93.3  747.14   103.1     749   112.9  750.31   132.6  750.98   142.4  750.98
   171.9  750.42   191.6  750.77   220.8  752.29   240.1  753.04   249.7     754
   259.3  756.16   268.9   759.3   278.5  763.14   288.2  767.36     317  780.98
   326.6  785.34   345.8  793.62   355.5  797.24   384.3  806.99   422.8  821.82
#Mann= 3 , 0 , 0
       0      .1       0    70.6    .045       0    93.3     .06       0
Bank Sta=70.6,93.3
XS Rating Curve= 0 ,0
Exp/Cntr=0.3,0.1

Type RM Length L Ch R = 1 ,9421.1  ,333.9,329.5,325.5
XS GIS Cut Line= 3
     1602832.331      351912.246      1602721.22      351874.052
     1602446.914      351868.843
#Sta/Elev= 30
       0  782.37     9.8  780.81    19.6  779.09    29.4  776.73    39.2  774.02
      49  771.15    58.8  768.11    68.5  764.93    97.9  754.93   107.7  751.29
   117.5   747.2   127.3  743.93   137.1  743.06   146.9  743.64   166.5  745.92
   176.3  746.81   186.1  747.58   195.9  748.15   205.7  748.54   215.5  748.74
   244.9  748.83   254.7  749.02   303.7  750.76   313.5  752.41   323.3  755.86
   342.9  763.95   362.4  771.87   372.2  775.47     382  778.17   391.8  779.72
#Mann= 3 , 0 , 0
       0      .1       0   127.3    .045       0   146.9     .06       0
Bank Sta=127.3,146.9
XS Rating Curve= 0 ,0
Exp/Cntr=0.3,0.1

Type RM Length L Ch R = 1 ,9091.6  ,348.6,333.3,317
XS GIS Cut Line= 3
     1602934.088      351515.923     1602579.049      351568.028
     1602425.621      351638.081
#Sta/Elev= 30
       0  813.65      97  780.32   145.5  764.65     194  748.73   203.7     745
   213.4  740.82   223.1  738.34   232.8  738.27   242.5  739.08   252.2   740.8
   261.9  742.27   271.6   743.5   281.2   744.5     291  745.25   300.6   745.8
     320  746.34   329.8  746.33   358.8   745.9   368.2  745.92   377.6  746.17
     387  746.67   396.3  747.49   405.7  749.17   415.1  752.67   424.4  756.99
   433.8  761.57   461.9  775.68   471.3  779.77   480.7  782.46   527.5  792.52
#Mann= 3 , 0 , 0
       0     .06       0   213.4    .045       0   242.5     .06       0
Bank Sta=213.4,242.5
XS Rating Curve= 0 ,0
Exp/Cntr=0.3,0.1

Type RM Length L Ch R = 1 ,8758.4  ,289,305.1,321.8
XS GIS Cut Line= 5
     1602944.003       351238.84     1602668.611      351245.537
     1602574.428      351347.651     1602513.957      351385.445
     1602384.541      351620.003
#Sta/Elev= 30
       0  816.89    19.7  813.01    39.4  808.08    88.6  793.48   137.7  780.16
   177.1  768.04   196.8  760.53   206.6  757.24   216.4  755.14     246  751.36
   312.5  741.89   340.3  739.27   349.6   738.4   358.8  738.22   368.1  738.25
   377.4  739.48   386.6   741.7   395.9  743.36   414.4  745.13     459  745.94
   485.7  747.73   495.3  749.15   504.8  751.26   533.5  758.92   543.1  760.69
   562.2  763.31   590.9  766.46   629.2  771.91   686.6  781.12   753.6  792.86
#Mann= 3 , 0 , 0
       0     .06       0   340.3    .045       0   377.4     .06       0
Bank Sta=340.3,377.4
XS Rating Curve= 0 ,0
Exp/Cntr=0.3,0.1

Type RM Length L Ch R = 1 ,8453.2  ,297.8,306.6,315.5
XS GIS Cut Line= 3
     1602819.654      351051.427     1602660.106      351041.899
     1602340.003      351068.254
#Sta/Elev= 30
       0  779.97    28.2  774.57    37.6  772.58      47  770.35    56.4  767.76
      94  756.78   103.4  753.92   122.2  747.92   131.6  745.62     141  744.47
   150.4   744.2     189  744.28   198.8  744.19   218.2  743.62   237.7  742.63
   247.4  741.95   286.4  738.68   296.1  738.21   305.8  738.55   309.1  739.03
   315.6  739.98   325.3  741.87     335  744.24   344.8  748.74   354.5  755.39
     374  769.89   383.7  775.93   393.4  779.98   451.8  797.86     481  805.88
#Mann= 3 , 0 , 0
       0     .06       0   286.4    .045       0   309.1     .07       0
Bank Sta=286.4,309.1
XS Rating Curve= 0 ,0
Exp/Cntr=0.3,0.1

Type RM Length L Ch R = 1 ,8146.6  ,146.3,144.6,142.6
XS GIS Cut Line= 3
     1602815.838        350883.6     1602610.109      350775.527
     1602391.359      350705.215
#Sta/Elev= 30
       0  776.44      29  768.88    48.4  763.31    77.5  754.66    87.2  752.44
    96.8  751.01   116.2  749.23   164.6  745.32   174.3  744.68   232.4  742.37
   251.5   741.1   261.1  740.23   270.7  739.11   289.8  736.02   299.4  735.37
     309  735.65   328.1  738.44   337.7  740.86   347.3  746.47   366.4  761.54
     376  767.84   385.6  772.66   395.1  776.59   404.7  780.04   414.3  782.71
   423.9  783.76   433.4  783.73     443  784.43   452.6  785.82   462.2  787.56
#Mann= 3 , 0 , 0
       0     .06       0   289.8    .045       0     309     .08       0
Bank Sta=289.8,309
XS Rating Curve= 0 ,0
Exp/Cntr=0.3,0.1