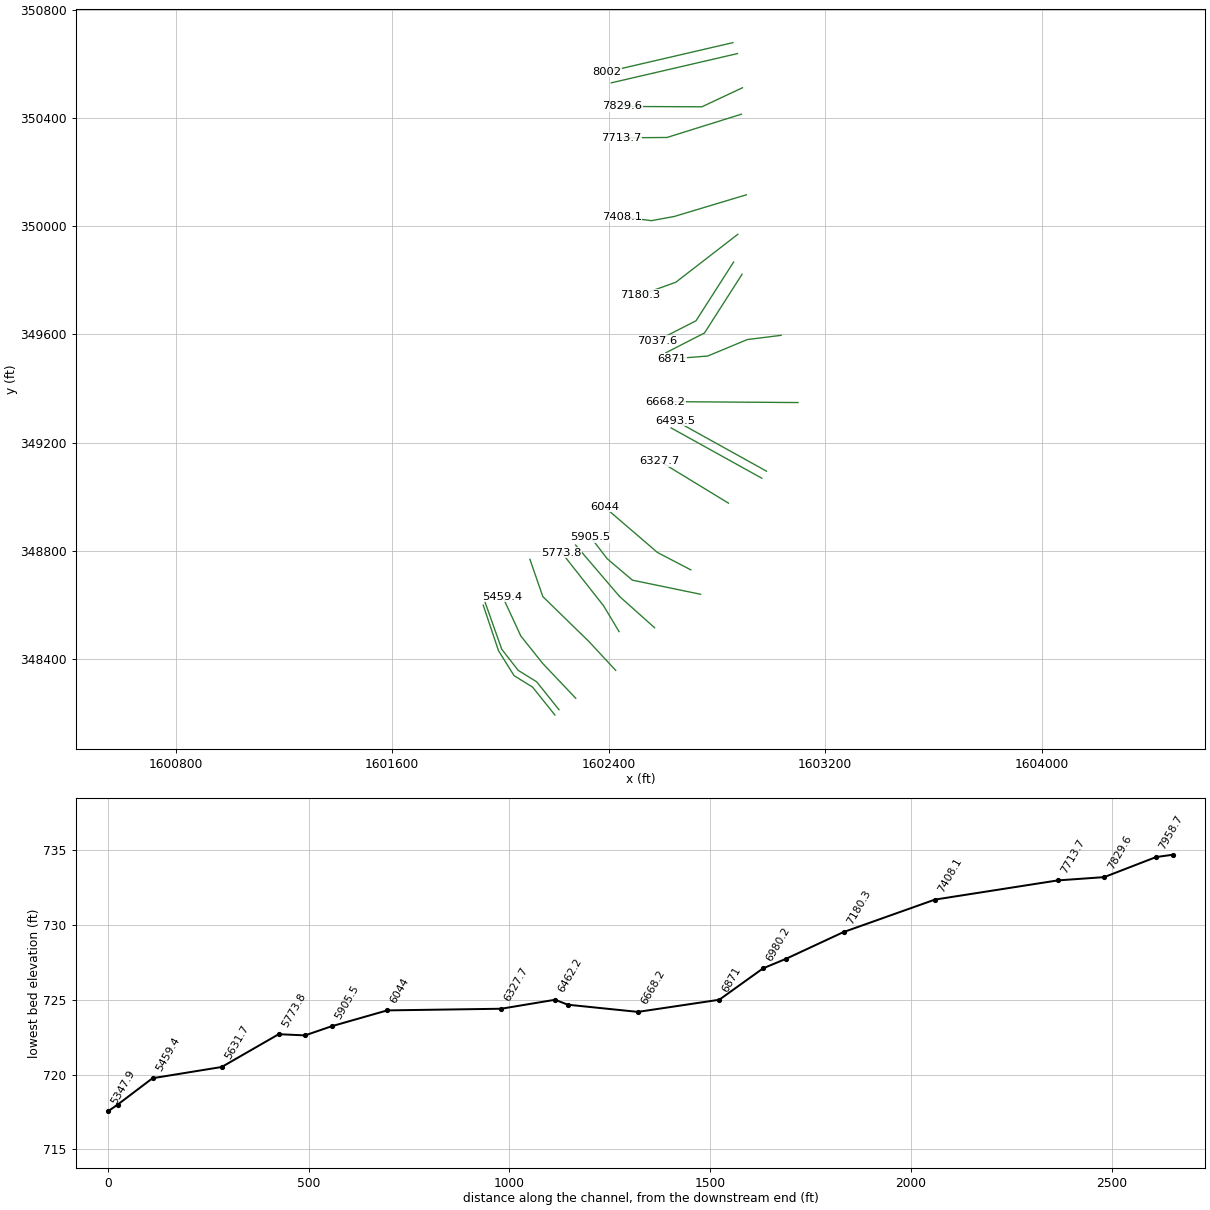
HEC-RAS study BIGRN.prj: BIGRN

--- BIGRN.g01 (geometry) --- (continued)

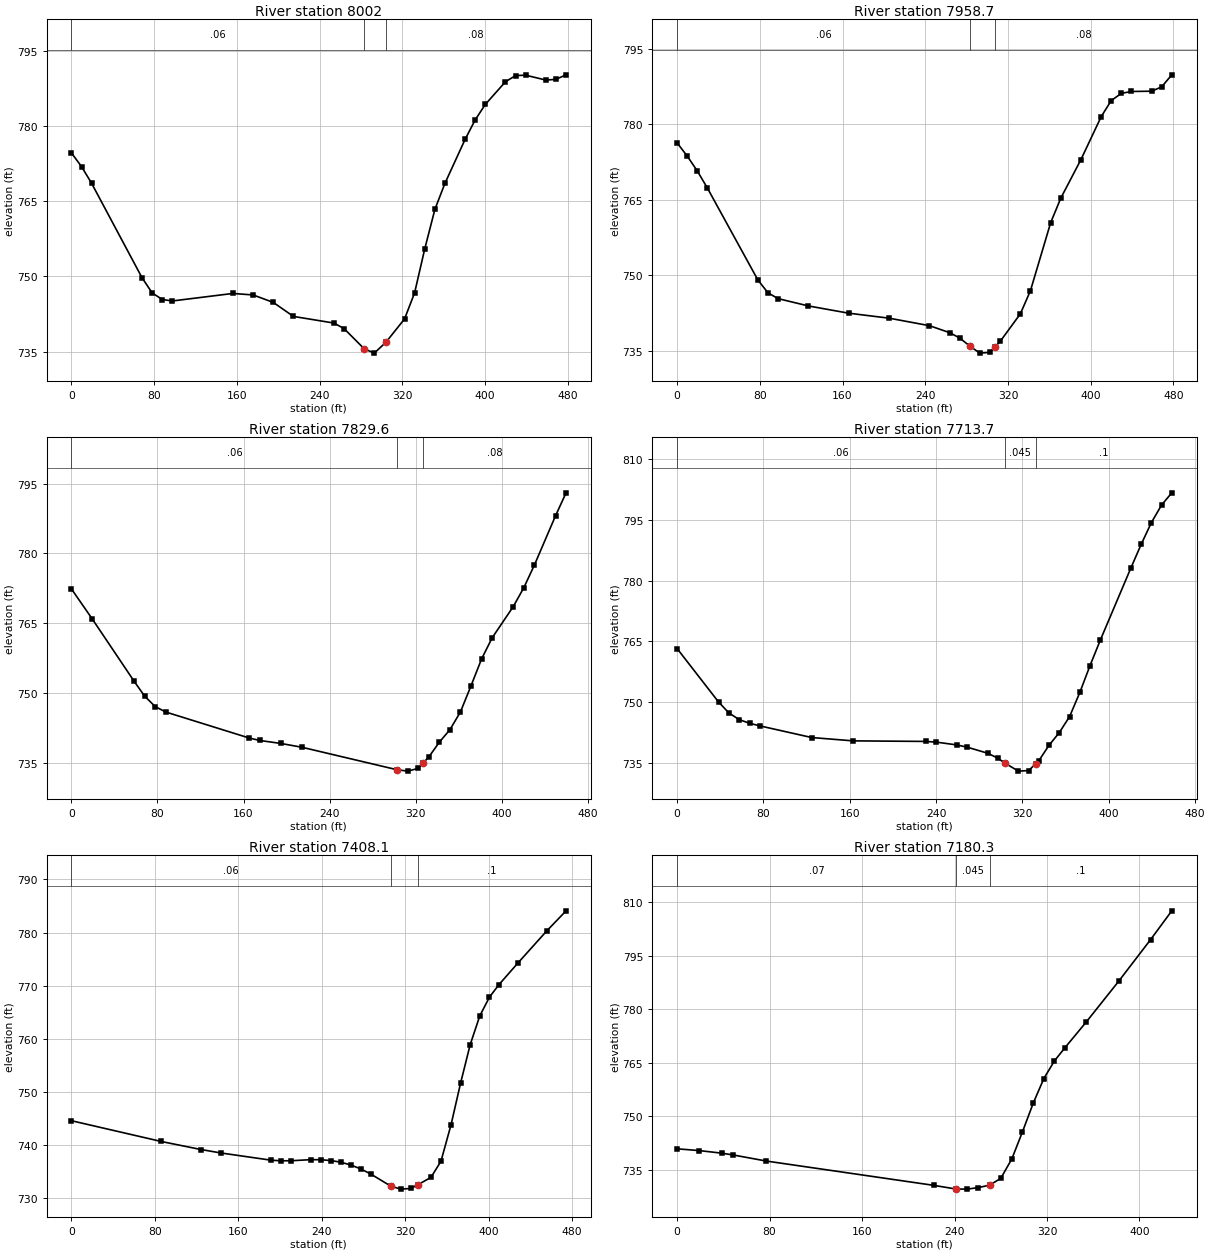
Type RM Length L Ch R = 1 ,8002    ,43.4,43.3,43.4
XS GIS Cut Line= 2
     1602858.807      350677.871     1602392.661      350569.798
#Sta/Elev= 30
       0  774.69     9.8  771.95    19.5  768.63    68.4  749.72    78.1  746.73
    87.9   745.4    97.7  745.11   156.2  746.61   175.8  746.31   195.3  744.82
   214.8  742.02   253.9   740.7   263.7   739.6   283.2  735.56     293  734.69
   304.2  736.85   322.3  741.53     332  746.74   341.8  755.51   351.6  763.39
   361.3  768.59   380.8  777.37   390.6  781.28   400.4  784.37   419.9   788.9
   429.7  790.13   439.4  790.21     459  789.23   468.7  789.38   478.5  790.28
#Mann= 3 , 0 , 0
       0     .06       0   283.2    .045       0   304.2     .08       0
Bank Sta=283.2,304.2
XS Rating Curve= 0 ,0
Exp/Cntr=0.3,0.1

Type RM Length L Ch R = 1 ,7958.7  ,134.3,129.1,123.8
XS GIS Cut Line= 2
     1602875.734      350637.507     1602409.588      350529.434
#Sta/Elev= 30
       0  776.28     9.8  773.65    19.5  770.71    29.3   767.3    78.1  749.06
    87.9   746.5    97.7  745.35     127   743.9     166  742.46   205.1  741.47
   244.1  739.98   263.7  738.59   273.4  737.52   283.2  735.92   292.8  734.53
   302.7  734.68   307.8  735.81   312.5  736.86     332  742.33   341.8  746.95
   361.3  760.42   371.1   765.3   390.6  772.96   410.2  781.49   419.9  784.68
   429.7  786.12   439.4  786.49     459  786.55   468.7  787.41   478.5   789.8
#Mann= 3 , 0 , 0
       0     .06       0   283.2    .045       0   307.8     .08       0
Bank Sta=283.2,307.8
XS Rating Curve= 0 ,0
Exp/Cntr=0.3,0.1

Type RM Length L Ch R = 1 ,7829.6  ,115.6,115.9,116.3
XS GIS Cut Line= 3
     1602893.963      350511.204     1602744.224      350440.892
     1602449.953      350442.194
#Sta/Elev= 26
       0  772.39    19.5  765.88    58.4  752.48    68.1  749.31    77.8  747.09
    87.6  745.91   165.4   740.3   175.2  739.78   194.8  739.14   214.5  738.31
   302.8  733.48   312.6  733.19   322.2  733.78  326.84734.9261   332.2  736.25
     342  739.44   351.8  742.11   361.6  745.95   371.4  751.56   381.2  757.32
     391  761.86   410.6  768.57   420.5  772.67   430.3  777.53   449.9   788.1
   459.7  793.05
#Mann= 3 , 0 , 0
       0     .06       0   302.8    .045       0  326.84     .08       0
Bank Sta=302.8,326.84
XS Rating Curve= 0 ,0
Exp/Cntr=0.3,0.1

Type RM Length L Ch R = 1 ,7713.7  ,301.7,305.6,309.4
XS GIS Cut Line= 3
     1602890.057      350413.548     1602615.317      350327.611
     1602444.744      350326.309
#Sta/Elev= 30
       0  763.21    38.4  750.03      48  747.33    57.6  745.67    67.2  744.78
    76.8  744.13   124.7  741.26   163.1  740.44   230.3   740.3   239.9  740.14
   259.1  739.44   268.7  738.89   287.9  737.38   297.3  736.15  303.37735.0063
   316.3  732.97   325.8  733.11   332.1  734.75   335.2  735.55   344.7  739.37
   354.2   742.5   363.7  746.44   373.2   752.4   382.6  759.01   392.1  765.27
   420.5  783.12     430  788.93   439.5  794.32     449  798.68   458.4  801.66
#Mann= 3 , 0 , 0
       0     .06       0  303.37    .045       0   332.1      .1       0
Bank Sta=303.37,332.1
XS Rating Curve= 0 ,0
Exp/Cntr=0.3,0.1

Type RM Length L Ch R = 1 ,7408.1  ,216.8,227.8,238.4
XS GIS Cut Line= 4
     1602908.286      350115.805     1602642.661      350035.944
     1602557.592      350020.319     1602448.217      350034.208
#Sta/Elev= 29
       0  744.57    86.1  740.66   124.3  739.14   143.5  738.49   191.3  737.14
   200.8  737.02   210.4  737.03   229.6  737.24   239.1  737.22   248.7  737.07
   258.2  736.76   267.8  736.23   277.4  735.49     287  734.53   306.2  732.24
   315.8  731.69   325.4  731.82   332.2  732.53   344.6   733.9   354.2  736.93
   363.9  743.84     373  751.64   382.2  758.88   391.4  764.29   400.6  767.81
   409.8  770.19   428.2  774.31   455.7  780.32   474.1  784.08
#Mann= 3 , 0 , 0
       0     .06       0   306.2    .045       0   332.2      .1       0
Bank Sta=306.2,332.2
XS Rating Curve= 0 ,0
Exp/Cntr=0.3,0.1

Type RM Length L Ch R = 1 ,7180.3  ,135.1,142.7,151.9
XS GIS Cut Line= 3
     1602877.036      349969.972     1602647.869      349792.888
     1602517.661      349746.013
#Sta/Elev= 21
       0  740.82    19.3  740.32    38.6   739.6    48.3  739.11    77.2  737.39
     222  730.58   241.3  729.55     251  729.52   260.6  729.95   270.3  730.63
     280  732.53   289.6  737.99   298.8  745.59   308.1  753.61   317.3  760.53
   326.5  765.49   335.7  769.22   354.2  776.46   381.9  787.74   409.6  799.45
     428  807.54
#Mann= 3 , 0 , 0
       0     .07       0   241.3    .045       0   270.3      .1       0
Bank Sta=241.3,270.3
XS Rating Curve= 0 ,0
Exp/Cntr=0.3,0.1

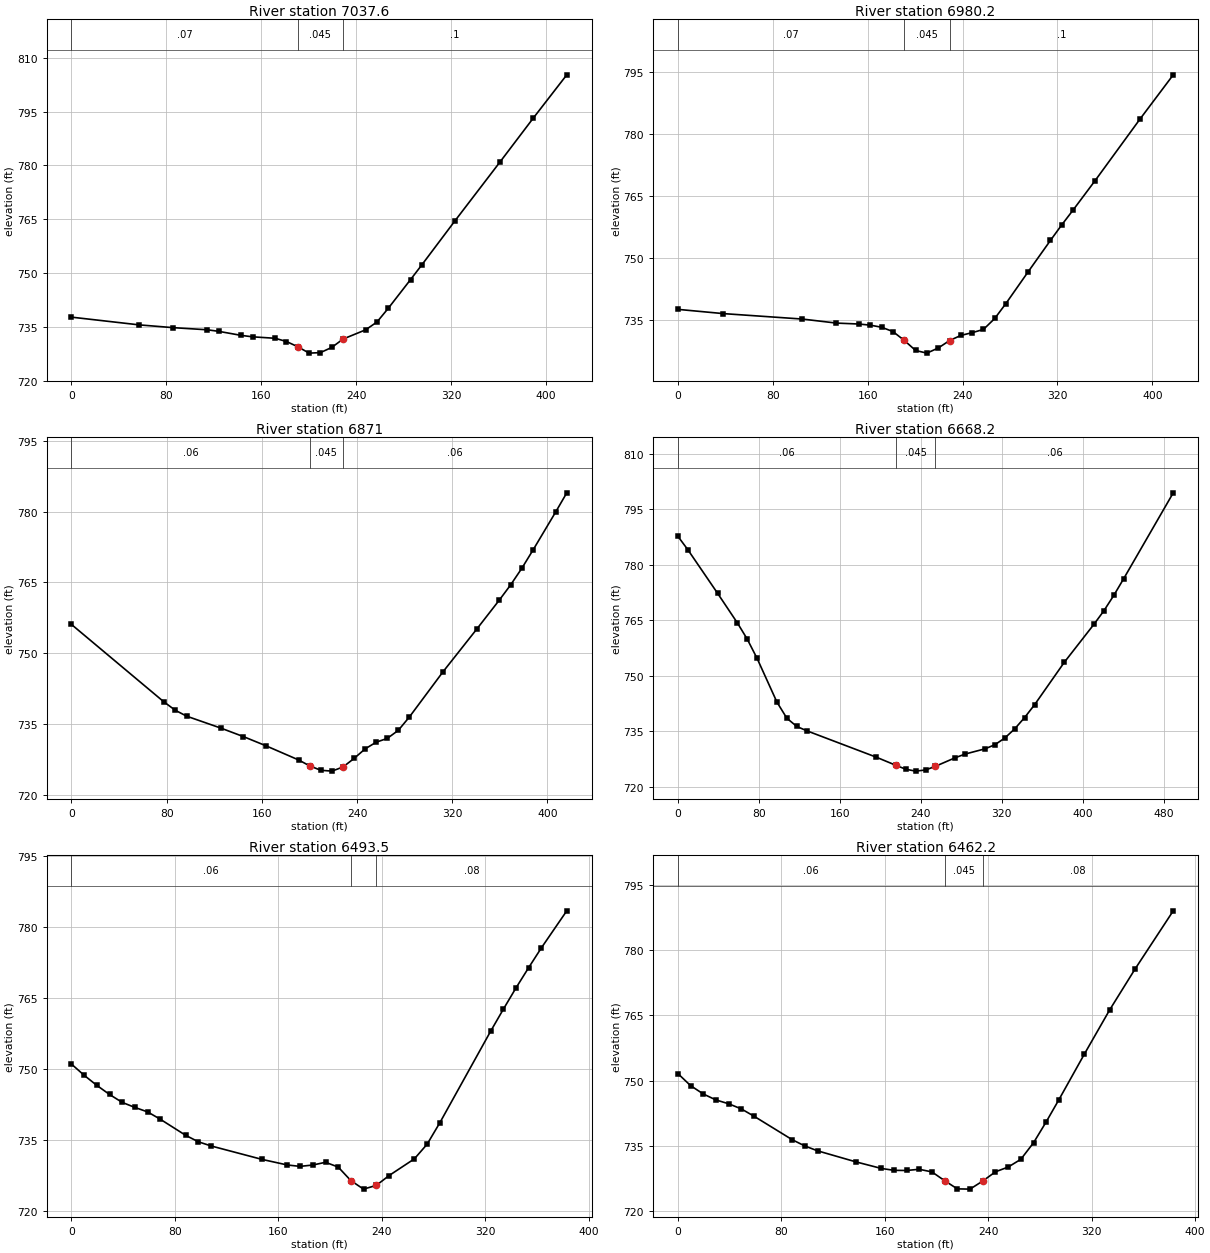
Type RM Length L Ch R = 1 ,7037.6  ,56.2,57.5,57.2
XS GIS Cut Line= 3
     1602861.411      349867.541     1602722.522      349650.527
     1602580.161      349577.611
#Sta/Elev= 23
       0  737.76    57.3   735.6    85.9  734.83   114.5  734.24   124.1  733.81
   143.1  732.68   152.7  732.28   171.8  731.87   181.3  730.97   190.8  729.52
   200.4  727.74   209.9  727.88   219.5  729.34     229  731.66   248.1  734.24
   257.6  736.41   267.1  740.22   285.9  748.22   295.3  752.27   323.5  764.65
   361.2  780.92   389.4   793.2   417.6  805.23
#Mann= 3 , 0 , 0
       0     .07       0   190.8    .045       0     229      .1       0
Bank Sta=190.8,229
XS Rating Curve= 0 ,0
Exp/Cntr=0.3,0.1

Type RM Length L Ch R = 1 ,6980.2  ,124.1,109.2,94.2
XS GIS Cut Line= 3
     1602892.661      349822.402     1602753.772      349605.388
     1602611.411      349532.472
#Sta/Elev= 25
       0  737.66    38.2  736.64     105  735.32   133.6  734.35   152.7  734.12
   162.2  733.85   171.8  733.34   181.3   732.3   190.8  730.18   200.4  727.74
   209.9   727.1   219.5  728.34     229  730.13   238.6  731.38   248.1  732.04
   257.6  732.82   267.1  735.46   276.5  739.06   295.3  746.74   314.1  754.31
   323.5  758.01   332.9  761.53   351.7  768.72   389.4  783.52   417.6  794.26
#Mann= 3 , 0 , 0
       0     .07       0   190.8    .045       0     229      .1       0
Bank Sta=190.8,229
XS Rating Curve= 0 ,0
Exp/Cntr=0.3,0.1

Type RM Length L Ch R = 1 ,6871    ,211.8,202.7,193.6
XS GIS Cut Line= 4
     1603036.758      349596.708     1602911.758      349581.083
     1602765.925      349520.319      1602633.98      349509.902
#Sta/Elev= 26
       0  756.09    77.5  739.72    87.2  737.91    96.9  736.64     126  734.08
   144.6  732.31   163.2   730.4     191  727.36   200.3   726.1   209.6  725.18
   218.9     725   228.2  725.87   237.5  727.68   246.8  729.71   256.1  731.13
   265.4  731.93   274.7  733.64     284  736.47   312.3  746.06   340.7  755.12
   359.6  761.25     369  764.43   378.5  767.98     388  771.89   406.9  779.89
   416.3  783.98
#Mann= 3 , 0 , 0
       0     .06       0   200.3    .045       0   228.2     .06       0
Bank Sta=200.3,228.2
XS Rating Curve= 0 ,0
Exp/Cntr=0.3,0.1

Type RM Length L Ch R = 1 ,6668.2  ,185.8,174.7,163.6
XS GIS Cut Line= 2
     1603099.258      349348.444     1602609.675      349351.916
#Sta/Elev= 30
       0  787.63     9.8  784.02    39.2  772.25    58.8  764.23    68.5  759.87
    78.3  754.64    97.9  742.83   107.7  738.48   117.5  736.26   127.3   735.1
   195.8  727.99   215.4  725.77   225.2   724.7     235  724.19   244.8   724.5
   254.6   725.5   274.2  727.82     284  728.81   303.6  730.22   313.3  731.32
   323.1  733.13   332.9  735.61   342.7  738.67   352.5  742.11   381.9  753.59
   411.3  763.89     421   767.5   430.8  771.65   440.6  776.18   489.6  799.38
#Mann= 3 , 0 , 0
       0     .06       0   215.4    .045       0   254.6     .06       0
Bank Sta=215.4,254.6
XS Rating Curve= 0 ,0
Exp/Cntr=0.3,0.1

Type RM Length L Ch R = 1 ,6493.5  ,31.3,31.4,31.3
XS GIS Cut Line= 2
     1602982.939      349094.972     1602647.869      349280.736
#Sta/Elev= 30
       0  751.05     9.8  748.69    19.6  746.56    29.5  744.63    39.3  742.96
    49.1   741.9    58.9  740.96    68.8   739.4    88.4  736.01    98.2  734.65
   108.1  733.77   147.4  730.94     167  729.76   176.8  729.47   186.6  729.75
   196.5  730.33   206.3  729.33   216.1  726.47   225.9  724.67   235.8  725.46
   245.6  727.52   265.2  731.05   275.1  734.15   284.9  738.66   324.2  757.97
     334   762.6   343.8   767.1   353.6  771.38   363.5  775.58   383.1  783.37
#Mann= 3 , 0 , 0
       0     .06       0   216.1    .045       0   235.8     .08       0
Bank Sta=216.1,235.8
XS Rating Curve= 0 ,0
Exp/Cntr=0.3,0.1

Type RM Length L Ch R = 1 ,6462.2  ,135.4,134.5,133.5
XS GIS Cut Line= 2
     1602965.578       349068.93     1602630.508      349254.694
#Sta/Elev= 30
       0   751.6     9.8  748.83    19.6  746.91    29.5  745.52    39.3  744.65
    49.1  743.46    58.9  741.78    88.4  736.38    98.2  734.93   108.1  733.81
   137.5  731.29   157.2  729.77     167  729.33   176.8  729.29   186.6  729.57
   196.5  728.96   206.3  726.94   216.1  725.06   225.9     725   235.8  726.87
   245.6  728.99   255.4  730.08   265.2  731.86   275.1   735.7   284.9  740.52
   294.7  745.61   314.4  756.11     334   766.3   353.6  775.69   383.1  789.07
#Mann= 3 , 0 , 0
       0     .06       0   206.3    .045       0   235.8     .08       0
Bank Sta=206.3,235.8
XS Rating Curve= 0 ,0
Exp/Cntr=0.3,0.1

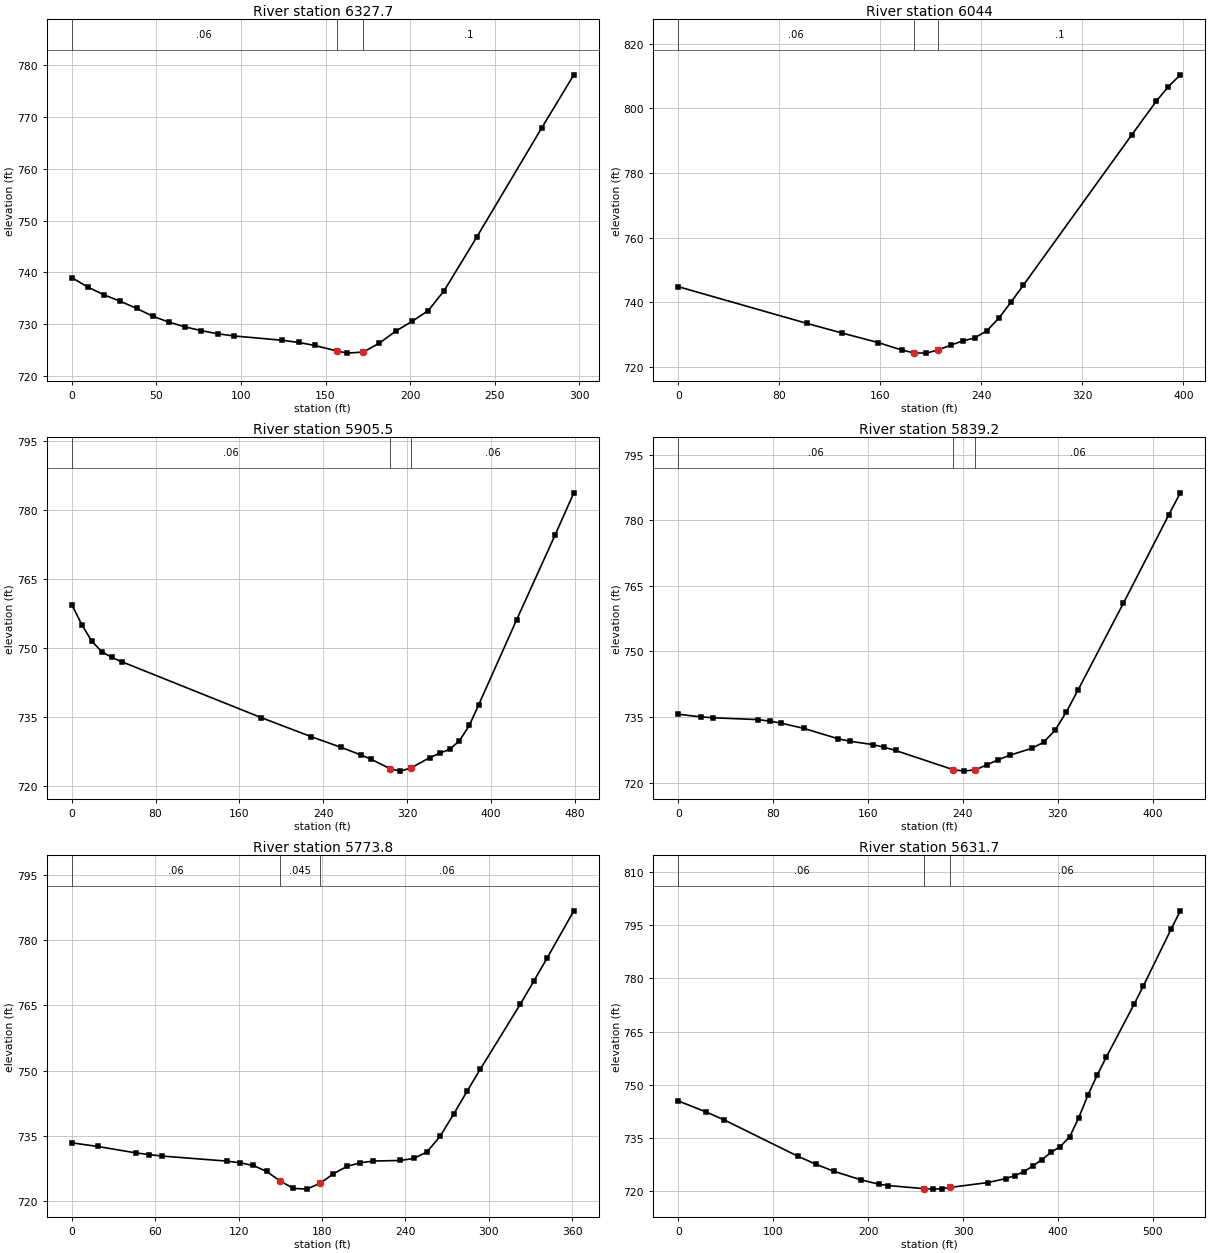
Type RM Length L Ch R = 1 ,6327.7  ,287.4,283.6,280.1
XS GIS Cut Line= 2
     1602842.314      348976.916     1602588.842       349131.43
#Sta/Elev= 25
       0  738.99     9.6  737.13    19.2  735.64    28.7  734.41    38.3  733.05
    47.9  731.51    57.5  730.39      67  729.46    76.6  728.74    86.2  728.14
    95.8  727.72   124.5  726.88   134.1  726.46   143.6  725.88   156.6  724.83
   162.8   724.4   172.4  724.61   181.9  726.35   191.5  728.64   201.1  730.52
   210.7   732.6   220.2  736.49   239.4  746.81   277.7  767.83   296.8  778.14
#Mann= 3 , 0 , 0
       0     .06       0   156.6    .045       0   172.4      .1       0
Bank Sta=156.6,172.4
XS Rating Curve= 0 ,0
Exp/Cntr=0.3,0.1

Type RM Length L Ch R = 1 ,6044    ,138.3,138.5,138.5
XS GIS Cut Line= 3
     1602703.425      348730.388     1602580.161      348794.625
      1602383.98      348963.027
#Sta/Elev= 19
       0  744.84   101.9  733.48   129.7   730.5   158.2  727.57   177.3  725.21
   186.9  724.34   196.4  724.29     206   725.3   215.6  726.74   225.2  728.04
   234.8  729.01   244.3   731.2   253.9  735.15   263.5  740.09   273.1  745.22
   359.2  791.87   378.4  802.15     388   806.7   397.5  810.36
#Mann= 3 , 0 , 0
       0     .06       0   186.9    .045       0     206      .1       0
Bank Sta=186.9,206
XS Rating Curve= 0 ,0
Exp/Cntr=0.3,0.1

Type RM Length L Ch R = 1 ,5905.5  ,70,66.3,62.8
XS GIS Cut Line= 4
     1602739.305      348640.328     1602487.568      348692.411
     1602394.252      348771.621     1602333.489      348850.831
#Sta/Elev= 23
       0  759.42     9.5  755.07      19  751.48    28.6  749.19    38.1  747.94
    47.6     747   180.9  734.85   228.5  730.72   257.1  728.39   275.9  726.76
   285.3  725.87   304.2  723.72   313.6  723.23   323.7  723.91   341.8  726.16
   351.2  727.11   360.6  727.96     370  729.78   379.5  733.15   388.5  737.67
   424.8  756.16   461.2  774.43   479.3  783.68
#Mann= 3 , 0 , 0
       0     .06       0   304.2    .045       0   323.7     .06       0
Bank Sta=304.2,323.7
XS Rating Curve= 0 ,0
Exp/Cntr=0.3,0.1

Type RM Length L Ch R = 1 ,5839.2  ,66.3,65.4,64.5
XS GIS Cut Line= 3
     1602569.457      348516.725     1602439.945      348632.333
     1602277.588      348822.074
#Sta/Elev= 26
       0  735.63    19.3  735.02    28.9  734.83    67.5   734.4    77.2  734.05
    86.8  733.59   106.1  732.38     135     730   144.7  729.46     164  728.69
   173.6  728.08   183.2  727.35   231.6  722.97   240.8  722.62   250.4  722.94
     260  724.01   269.6  725.22   279.3  726.23   298.5  727.87   308.1  729.24
   317.7  731.96   327.3  736.19   336.9  741.09   375.3  761.02   413.7  781.29
   423.3  786.27
#Mann= 3 , 0 , 0
       0     .06       0   231.6    .045       0   250.4     .06       0
Bank Sta=231.6,250.4
XS Rating Curve= 0 ,0
Exp/Cntr=0.3,0.1

Type RM Length L Ch R = 1 ,5773.8  ,139.1,142,145
XS GIS Cut Line= 3
     1602438.234      348502.307     1602380.942      348597.793
     1602226.428      348793.974
#Sta/Elev= 28
       0  733.36    18.6  732.52    46.4  731.02    55.7  730.65      65  730.31
   111.4  729.15     121  728.76   130.6  728.14   140.2  726.76   149.8  724.57
   159.4  722.87     169   722.7   178.6  724.04   188.2  726.24   197.8  727.91
   207.4  728.77     217  729.16   236.2   729.3   245.8  729.75   255.4  731.24
     265  734.89   274.6  739.94   284.2  745.17   293.8  750.29   322.7  765.32
   332.3  770.55   341.9   775.9   361.1  786.75
#Mann= 3 , 0 , 0
       0     .06       0   149.8    .045       0   178.6     .06       0
Bank Sta=149.8,178.6
XS Rating Curve= 0 ,0
Exp/Cntr=0.3,0.1

Type RM Length L Ch R = 1 ,5631.7  ,175.5,172.3,169.8
XS GIS Cut Line= 4
     1602425.719      348359.295     1602326.978      348465.632
     1602156.622      348631.647     1602108.879      348769.451
#Sta/Elev= 30
       0   745.4      29  742.34    48.4  740.05   125.8  729.82   145.1  727.52
   164.1  725.53   192.7  723.12   211.7  721.87   221.2  721.53   259.3  720.63
   268.8  720.51   278.3  720.64   286.6     721   325.9  722.36   344.9  723.48
   354.4   724.3     364  725.46   373.5  727.04     383  728.84   392.7  730.89
   402.4  732.54   412.2  735.24   421.9  740.73   431.6   747.1   441.3  752.73
     451  757.85   480.2  772.75   489.9  777.89   519.1   793.9   528.8  799.08
#Mann= 3 , 0 , 0
       0     .06       0   259.3    .045       0   286.6     .06       0
Bank Sta=259.3,286.6
XS Rating Curve= 0 ,0
Exp/Cntr=0.3,0.1

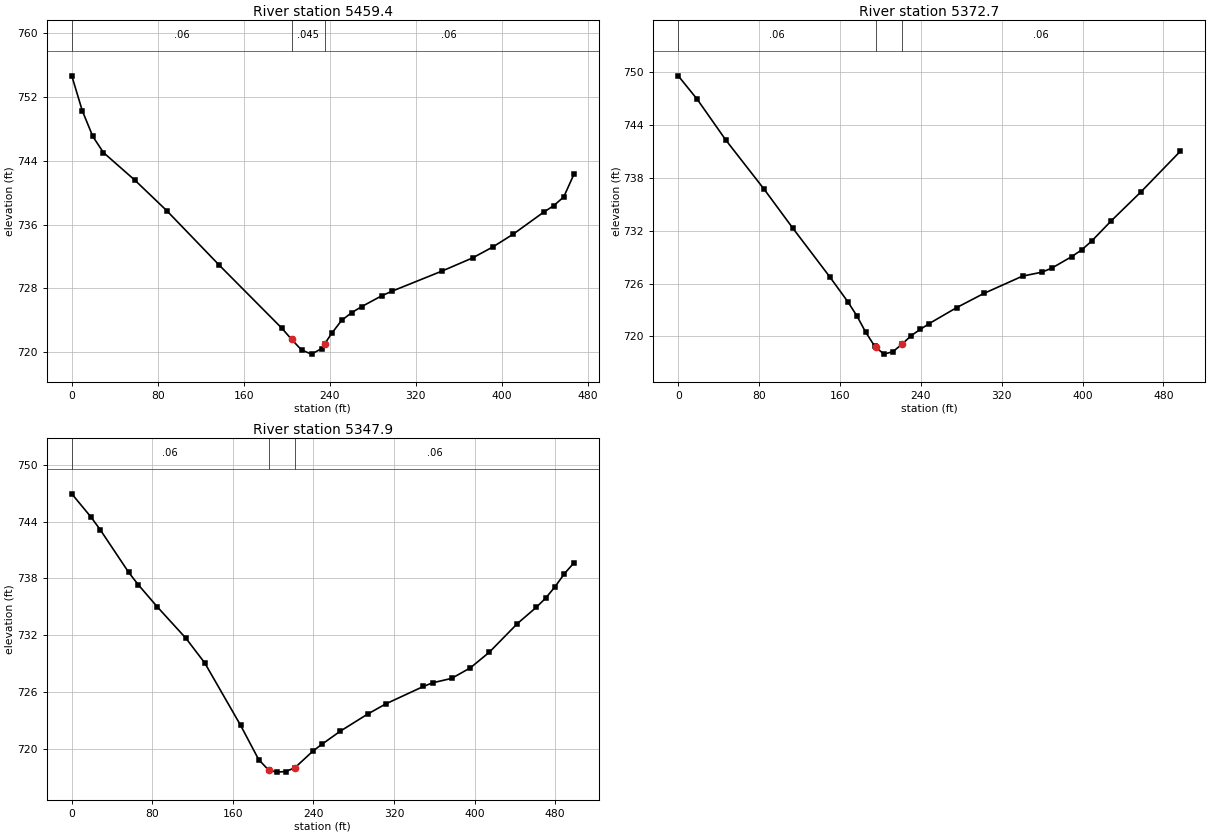
Type RM Length L Ch R = 1 ,5459.4  ,78.6,86.7,89.1
XS GIS Cut Line= 4
      1602278.15      348256.213     1602156.622      348384.251
     1602075.242      348486.248     1602007.968      348631.647
#Sta/Elev= 27
       0  754.64     9.8  750.26    19.6  747.04    29.4  745.03    58.8  741.55
    88.3  737.75   137.3   730.9   195.2  723.05   204.5  721.62   213.8  720.28
   223.1  719.76   232.4  720.45   235.2  721.02   241.8  722.35   251.1  723.99
   260.4  724.95   269.7  725.71   288.4  727.07   297.7  727.63   344.7  730.18
     373  731.82   391.8  733.19   410.7  734.79     439  737.54   448.4  738.36
   457.8  739.46   467.2  742.28
#Mann= 3 , 0 , 0
       0     .06       0   204.5    .045       0   235.2     .06       0
Bank Sta=204.5,235.2
XS Rating Curve= 0 ,0
Exp/Cntr=0.3,0.1

Type RM Length L Ch R = 1 ,5372.7  ,24.7,24.8,23.4
XS GIS Cut Line= 5
     1602216.301      348213.895     1602133.836      348316.977
     1602065.476      348359.295     1602004.713       348437.42
     1601942.864      348612.116
#Sta/Elev= 28
       0  749.54    18.9  746.86    47.2  742.24    84.9   736.7   113.2   732.3
   149.9  726.76   167.7  723.95   176.7  722.34   185.6  720.46   194.5  718.87
   195.2   718.8   203.5     718   212.4  718.28   221.4  719.13   230.4  720.09
   239.4   720.8   248.4  721.47   275.4  723.27   302.4  724.88   340.6  726.84
   360.2   727.3   369.9  727.77   389.4  729.06   399.2  729.82   408.9   730.8
   428.4  733.11   457.7  736.38   496.7  740.99
#Mann= 3 , 0 , 0
       0     .06       0   195.2    .045       0   221.4     .06       0
Bank Sta=195.2,221.4
XS Rating Curve= 0 ,0
Exp/Cntr=0.3,0.1

Type RM Length L Ch R = 1 ,5347.9  ,45.7,32.8,26.3
XS GIS Cut Line= 5
      1602201.11      348194.364     1602118.645      348297.446
     1602050.285      348339.763     1601992.777      348431.994
     1601936.353       348600.18
#Sta/Elev= 30
       0  746.94    18.9  744.51    28.3  743.14    56.6  738.63      66  737.34
    84.9     735   113.2   731.7     132  729.08   167.7  722.47   185.6  718.86
   195.4  717.76   203.5  717.54   212.4   717.6   221.5     718   239.6  719.78
   248.6   720.5   266.8  721.88   293.9  723.68     312  724.76   349.1  726.59
   358.4  726.98   377.1  727.44   395.8  728.56   414.5   730.2   442.5  733.24
   461.2  734.95   470.5  735.92   479.8  737.12   489.2  738.51   498.5  739.64
#Mann= 3 , 0 , 0
       0     .06       0   195.4    .045       0   221.5     .06       0
Bank Sta=195.4,221.5
XS Rating Curve= 0 ,0
Exp/Cntr=0.3,0.1