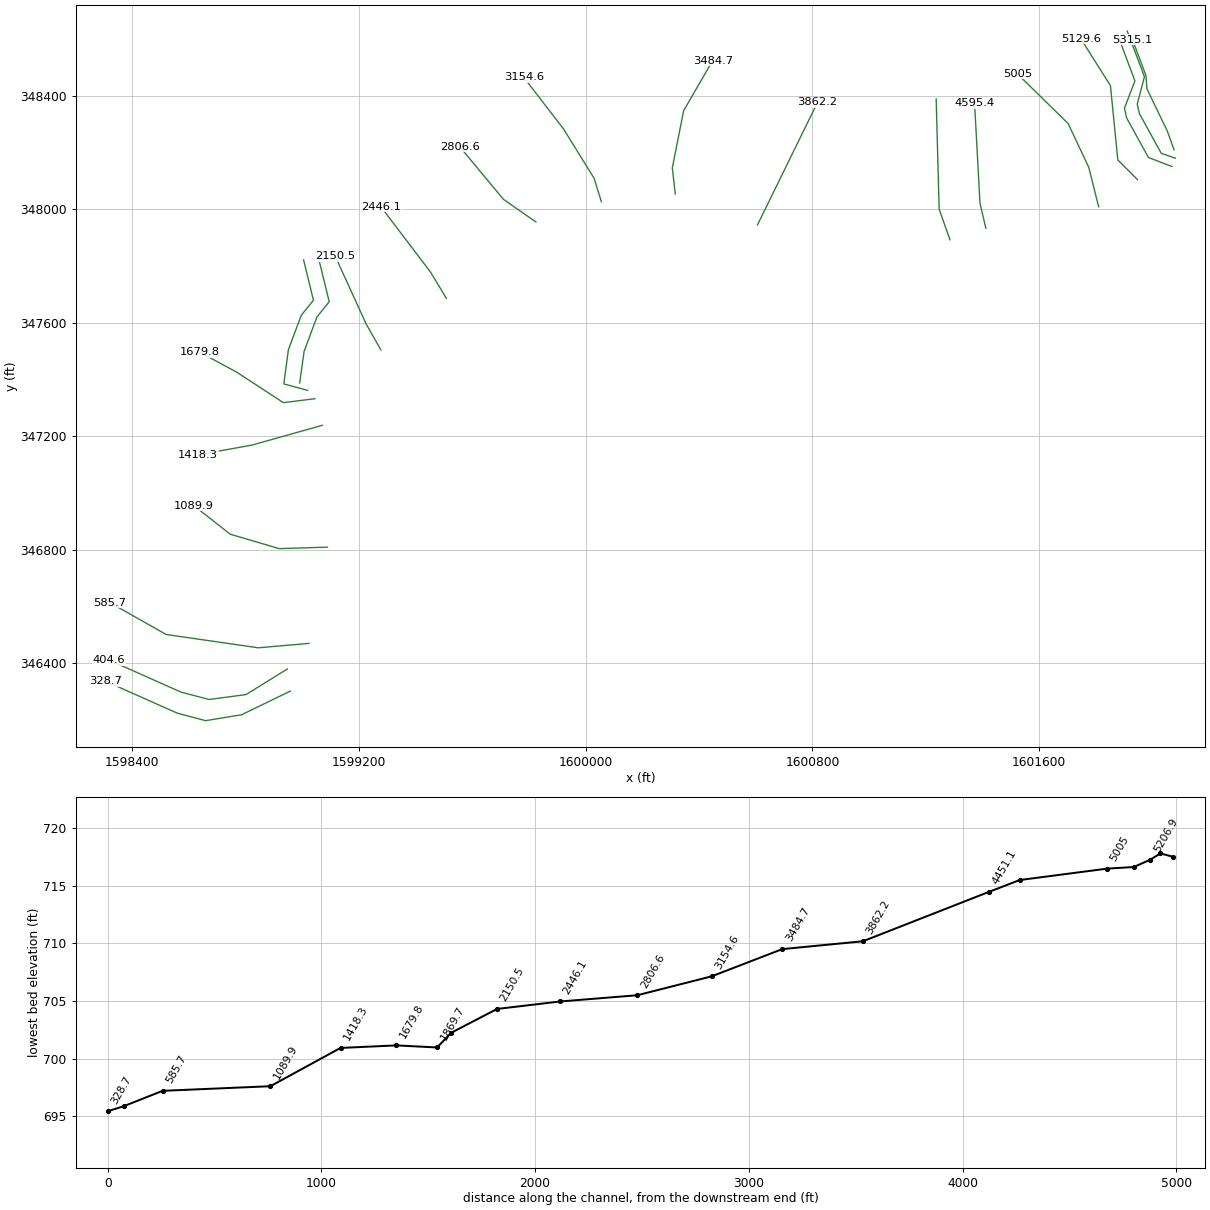
HEC-RAS study BIGRN.prj: BIGRN

--- BIGRN.g01 (geometry) --- (continued)

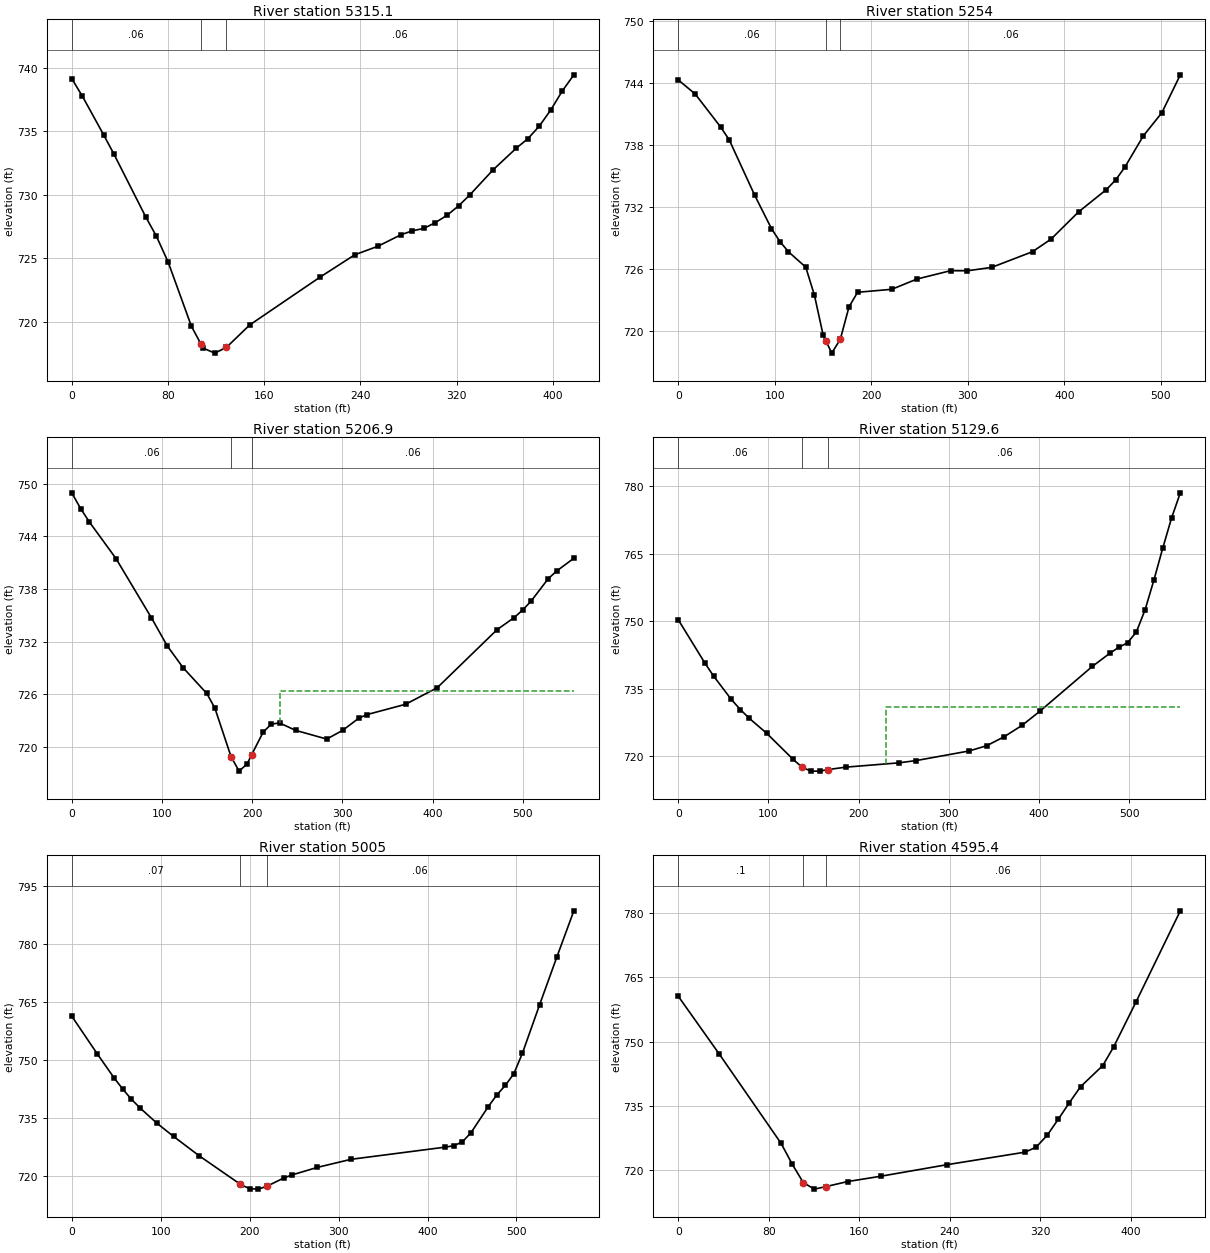
Type RM Length L Ch R = 1 ,5315.1  ,60.5,61,61.4
XS GIS Cut Line= 5
     1602075.513      348209.555     1602051.642      348275.744
     1601980.027      348424.399     1601976.164      348472.229
     1601928.942      348597.923
#Sta/Elev= 30
       0  739.14     8.8  737.76    26.4  734.73    35.2  733.17    61.6  728.23
    70.4  726.72    80.1   724.7    99.5  719.63   107.3  718.25   109.2  717.91
   118.9  717.51   128.6  717.96     148  719.73   206.2  723.48   235.4  725.26
   254.6  725.93   273.8  726.84   283.4  727.15   292.9  727.34   302.5   727.8
   312.1  728.37   321.7  729.11   331.3     730   350.5  731.96   369.7  733.66
   379.3   734.4   388.8  735.39   398.4  736.67     408  738.17   417.6  739.44
#Mann= 3 , 0 , 0
       0     .06       0   107.3    .045       0   128.6     .06       0
Bank Sta=107.3,128.6
XS Rating Curve= 0 ,0
Exp/Cntr=0.3,0.1

Type RM Length L Ch R = 1 ,5254    ,47.2,47.1,47.2
XS GIS Cut Line= 6
     1602080.175      348180.016     1602030.324      348197.334
     1601953.284      348337.308     1601945.689      348370.946
     1601971.095      348467.261     1601910.495      348628.457
#Sta/Elev= 30
       0  744.26    17.6  742.89      44  739.69    52.8  738.46    79.1  733.11
    96.6  729.86   105.4   728.6   114.2  727.62   132.1  726.13   141.1  723.41
     150   719.6   152.9  719.02     159  717.81   167.9  719.15   176.9  722.29
   185.8   723.7   221.3  723.99   247.2  724.98   282.1  725.79   299.5  725.78
   324.7  726.11     367  727.63   386.1  728.84   414.8  731.49   443.5  733.64
   453.1  734.57   462.7  735.82   481.8  738.84   500.9  741.07   520.1  744.75
#Mann= 3 , 0 , 0
       0     .06       0   152.9    .045       0   167.9     .06       0
Bank Sta=152.9,167.9
XS Rating Curve= 0 ,0
Exp/Cntr=0.3,0.1

Type RM Length L Ch R = 1 ,5206.9  ,85.8,77.3,68.8
XS GIS Cut Line= 6
     1602067.647      348150.961     1601985.181      348182.428
     1601908.141      348322.402     1601900.546       348356.04
     1601937.438      348452.611     1601877.759      348612.116
#Sta/Elev= 30
       0  748.96     9.8  747.17    19.6  745.63      49  741.48    88.3  734.73
   105.8  731.54   123.4  729.05   149.7  726.11   158.6  724.46   176.6  718.91
   185.5  717.27   194.5   718.1   199.5  719.16   212.4  721.75   221.3  722.62
   230.3  722.76   248.2  721.91   282.7  720.92   300.4  721.92   318.2   723.3
     327   723.7     370  724.88   405.2  726.77   471.4  733.37   490.4  734.75
   499.8  735.61   509.3  736.64   528.2  739.18   537.6  740.06   556.6  741.51
#Mann= 3 , 0 , 0
       0     .06       0   176.6    .045       0   199.5     .06       0
#XS Ineff= 2 , 0
                          230.31          726.38
Permanent Ineff=
       F       F
Bank Sta=176.6,199.5
XS Rating Curve= 0 ,0
Exp/Cntr=0.3,0.1

Type RM Length L Ch R = 1 ,5129.6  ,116.5,124.6,132.7
XS GIS Cut Line= 4
      1601946.65       348104.39     1601877.206      348173.835
     1601851.164      348435.987     1601746.998      348600.918
#Sta/Elev= 30
       0  750.33    29.5  740.69    39.3  737.76    58.9  732.57    68.8  730.34
    78.6  728.41    98.2  725.03   127.5  719.22   137.2  717.52     147  716.63
   156.8  716.63   166.5  716.99     186  717.52   244.6  718.47   264.1  718.99
   322.6  721.12   342.1  722.29   361.6  724.31   381.2  726.81   400.7  729.91
   459.2  739.94   478.7  742.88   488.4  744.17   498.2   745.2     508  747.61
   517.7  752.57   527.5   759.2   537.2  766.24     547  772.96   556.7  778.56
#Mann= 3 , 0 , 0
       0     .06       0   137.2    .045       0   166.5     .06       0
#XS Ineff= 2 , 0
                          230.31             731
Permanent Ineff=
       F       F
Bank Sta=137.2,166.5
XS Rating Curve= 0 ,0
Exp/Cntr=0.3,0.1

Type RM Length L Ch R = 1 ,5005    ,418.7,409.5,400.3
XS GIS Cut Line= 4
     1601809.498      348008.904     1601774.775      348147.793
     1601701.859      348302.307     1601523.039      348477.654
#Sta/Elev= 30
       0  761.33    28.6  751.58    47.7  745.29    57.3  742.43    66.8  739.86
    76.4  737.61    95.4  733.64   114.5  730.14   143.2  725.14   188.9  717.85
   190.6  717.58   200.1  716.61   209.6  716.49   219.1   717.2   238.1  719.35
   247.6  720.17     276  722.12     314  724.22     420  727.38   429.6  727.75
   439.2  728.75   448.9  731.13   468.1  737.81   477.8  740.89   487.4  743.36
     497   746.4   506.7  751.74   525.9  764.22   545.2  776.55   564.5  788.64
#Mann= 3 , 0 , 0
       0     .07       0   188.9    .045       0   219.1     .06       0
Bank Sta=188.9,219.1
XS Rating Curve= 0 ,0
Exp/Cntr=0.3,0.1

Type RM Length L Ch R = 1 ,4595.4  ,144.9,144.3,143.7
XS GIS Cut Line= 3
     1601411.928      347932.515     1601391.095      348021.057
     1601371.998      348373.487
#Sta/Elev= 20
       0   760.6    36.4  747.03      91  726.17   100.8  721.32   110.6  717.01
   120.4   715.5   130.2  716.07   149.8  717.27   179.2  718.52     238  721.23
   306.6  724.14   316.4   725.3   326.3  728.12   336.1  731.88   345.9  735.74
   355.7  739.45   375.3  744.37   385.1  748.81   404.7  759.24   443.9  780.56
#Mann= 3 , 0 , 0
       0      .1       0   110.6    .045       0   130.2     .06       0
Bank Sta=110.6,130.2
XS Rating Curve= 0 ,0
Exp/Cntr=0.3,0.1

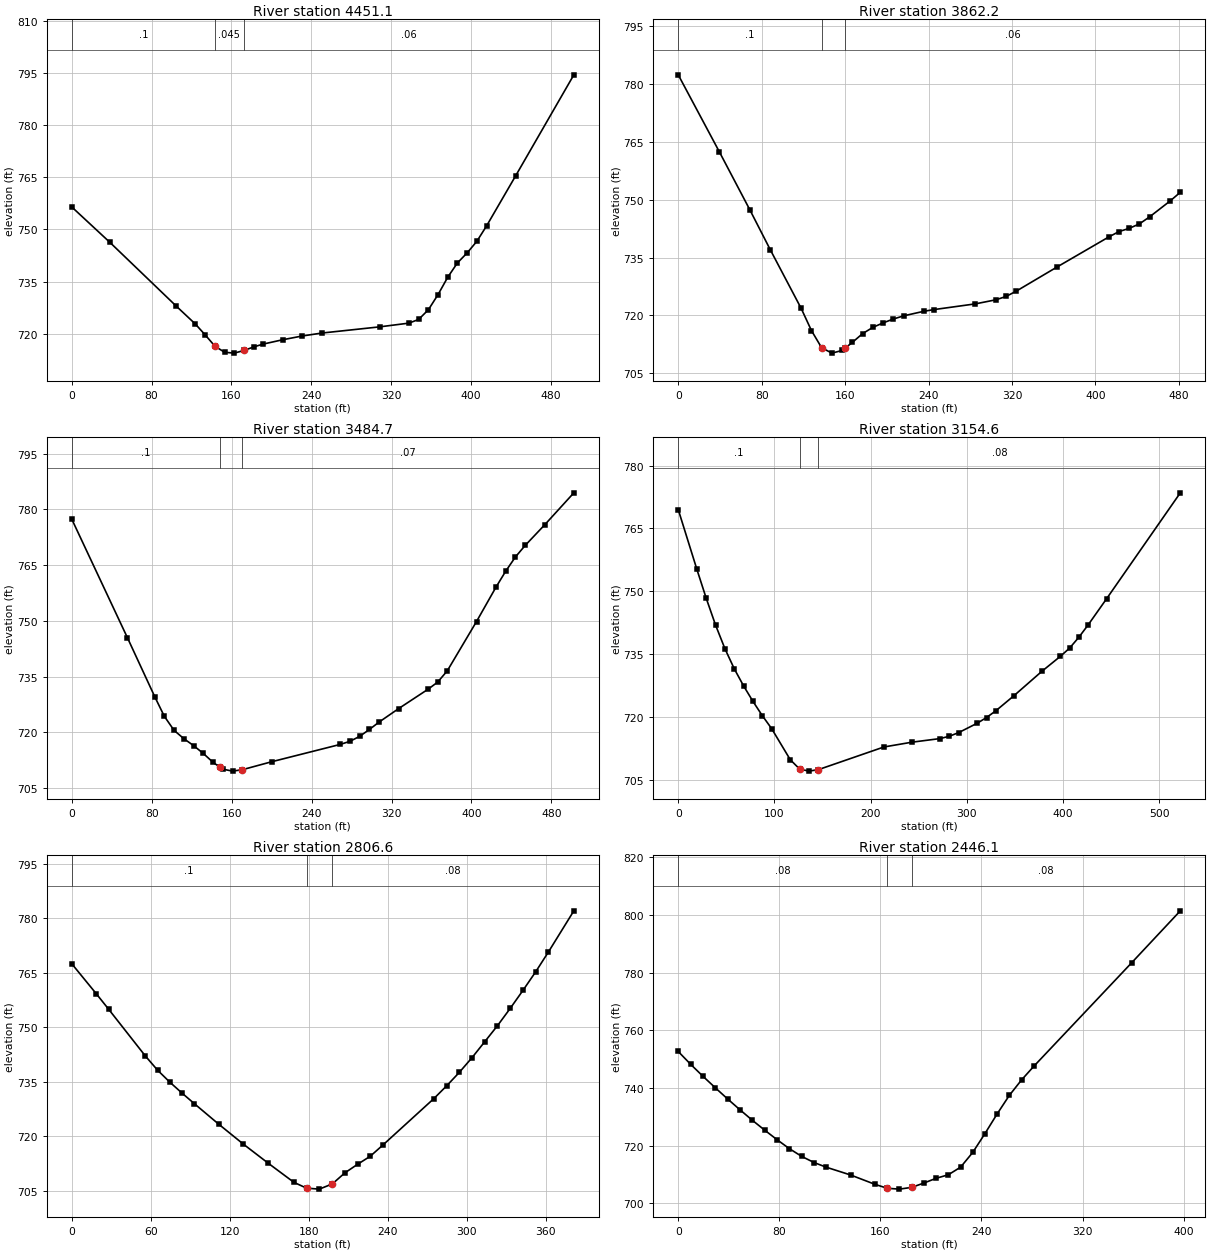
Type RM Length L Ch R = 1 ,4451.1  ,599.9,589,578.1
XS GIS Cut Line= 3
     1601285.192      347892.585     1601246.998      348000.224
     1601236.581      348389.112
#Sta/Elev= 26
       0  756.46    38.1  746.32   104.7  727.98   123.9  722.82   133.7  719.71
   143.4  716.49   153.1  714.72   162.8  714.47   172.6  715.23   182.3  716.25
     192  717.08   211.5  718.32   230.9  719.39   250.4  720.23   308.7  722.02
   337.9  723.09   347.6  724.14   357.4  726.93   367.1  731.29   376.8  736.27
   386.5  740.38   396.3  743.28     406   746.6   415.7     751   444.9  765.42
   503.2  794.42
#Mann= 3 , 0 , 0
       0      .1       0   143.4    .045       0   172.6     .06       0
Bank Sta=143.4,172.6
XS Rating Curve= 0 ,0
Exp/Cntr=0.3,0.1

Type RM Length L Ch R = 1 ,3862.2  ,371.6,377.4,383.3
XS GIS Cut Line= 2
     1600606.373      347944.668     1600818.178       348376.96
#Sta/Elev= 30
       0  782.45    39.3  762.52    68.8  747.33    88.4  736.96   117.9  721.79
   127.7  716.06   137.5  711.58   147.4  710.19   157.2  710.89   160.3  711.55
     167  712.99   176.8  715.26   186.7  716.89   196.5  718.05   206.3  719.05
   216.1  719.87   235.8  721.07   245.6  721.51   284.9  722.98   304.6  724.04
   314.4  724.91   324.2   726.3   363.5   732.6   412.6  740.32   422.4  741.73
   432.3  742.58   442.1  743.73   451.9  745.56   471.6  749.69   481.4  751.95
#Mann= 3 , 0 , 0
       0      .1       0   137.5    .045       0   160.3     .06       0
Bank Sta=137.5,160.3
XS Rating Curve= 0 ,0
Exp/Cntr=0.3,0.1

Type RM Length L Ch R = 1 ,3484.7  ,312.7,330.1,347.3
XS GIS Cut Line= 4
     1600316.442      348054.043     1600306.025      348146.057
     1600345.956      348347.446     1600448.387      348524.529
#Sta/Elev= 30
       0   777.4    55.6  745.51    83.3  729.42    92.6   724.3   102.4  720.49
   112.2  718.25   121.9  716.39   131.7  714.26   141.5  711.85   148.4  710.57
   151.3  710.03     161  709.51   170.8   709.9   200.1  712.04   268.6   716.7
   278.4  717.54   288.1  718.87   297.9  720.74   307.6  722.73   327.1  726.35
   356.4  731.54   366.1  733.47   375.8  736.52   405.1  749.82   424.6  759.09
   434.3  763.37     444   767.2   453.8  770.32   473.3  775.86   502.5  784.49
#Mann= 3 , 0 , 0
       0      .1       0   148.4    .045       0   170.8     .07       0
Bank Sta=148.4,170.8
XS Rating Curve= 0 ,0
Exp/Cntr=0.3,0.1

Type RM Length L Ch R = 1 ,3154.6  ,345.1,348,350.5
XS GIS Cut Line= 4
     1600056.025      348026.265     1600029.984      348109.599
     1599922.345       348283.21      1599781.72      348465.501
#Sta/Elev= 30
       0  769.51    19.4  755.24    29.1  748.35    38.8  741.97    48.5  736.35
    58.2  731.56    67.9  727.48    77.6   723.8    87.3   720.4      97  717.31
   116.5  709.85   126.2  707.64   135.9  707.15   145.7  707.51   213.8  712.91
   242.9  714.05   272.1  714.91   281.8  715.47   291.6  716.35   310.8  718.58
   320.4  719.93     330  721.52   349.1  725.17   377.9  730.94   397.1  734.51
   406.7  736.47   416.3  739.05   425.9  741.98   445.1  748.22   521.8   773.5
#Mann= 3 , 0 , 0
       0      .1       0   126.2    .045       0   145.7     .08       0
Bank Sta=126.2,145.7
XS Rating Curve= 0 ,0
Exp/Cntr=0.3,0.1

Type RM Length L Ch R = 1 ,2806.6  ,361.8,360.5,359.5
XS GIS Cut Line= 3
     1599825.123      347955.085     1599710.539      348034.946
     1599556.025       348220.71
#Sta/Elev= 30
       0  767.49    18.6  759.25    27.9  755.03    55.9  742.12    65.2  738.21
    74.5  734.92    83.8   731.9    93.1  729.01   111.7  723.34   130.4  717.86
   149.3  712.61   168.7  707.38   178.3  705.78     188  705.51   197.9  706.95
   207.3  709.95     217  712.33   226.6  714.53   236.3  717.64     275  730.41
   284.6  733.88   294.3  737.61     304  741.68   313.6  746.04   323.3  750.46
     333  755.23   342.6  760.14   352.3  765.27     362  770.74   381.3  782.05
#Mann= 3 , 0 , 0
       0      .1       0   178.3    .045       0   197.9     .08       0
Bank Sta=178.3,197.9
XS Rating Curve= 0 ,0
Exp/Cntr=0.3,0.1

Type RM Length L Ch R = 1 ,2446.1  ,300.2,295.7,290.6
XS GIS Cut Line= 3
      1599509.15      347685.987     1599453.595      347778.001
     1599278.248      348008.904
#Sta/Elev= 30
       0  752.66     9.8  748.23    19.5   744.1    29.3   740.1    39.1  736.21
    48.9  732.45    58.6  728.85    68.4  725.41    78.2  722.11    87.9  719.01
    97.7  716.32   107.5  714.18   117.2  712.56   136.5  709.86   155.8  706.62
   165.5  705.26   175.1  704.97   184.8  705.58   194.5  707.09   204.1  708.72
   213.8  709.95   223.5  712.59   233.1  717.68   242.8  724.23   252.4  731.02
   262.1  737.47   271.8  742.84   281.4  747.51   358.8  783.36   397.4   801.4
#Mann= 3 , 0 , 0
       0     .08       0   165.5    .045       0   184.8     .08       0
Bank Sta=165.5,184.8
XS Rating Curve= 0 ,0
Exp/Cntr=0.3,0.1

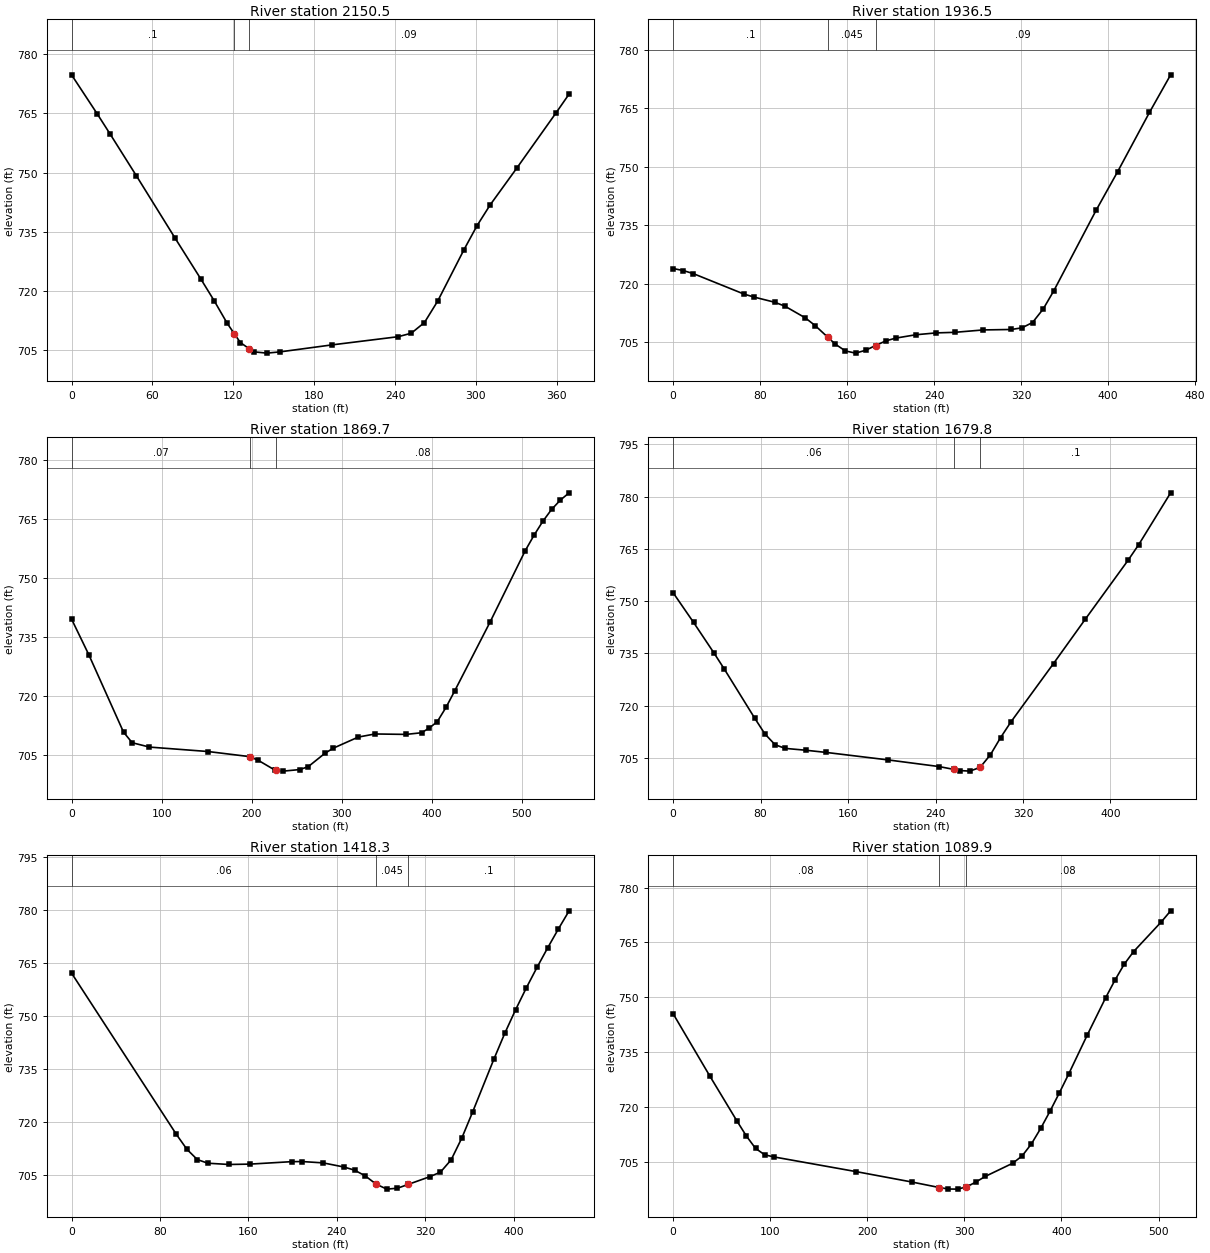
Type RM Length L Ch R = 1 ,2150.5  ,233.9,214,191.8
XS GIS Cut Line= 3
     1599278.248      347503.696     1599226.164       347595.71
     1599116.789      347835.293
#Sta/Elev= 25
       0  774.77    19.2  764.81    28.8  759.68    48.1  749.21    76.9  733.38
    96.1  722.98   105.7  717.64   115.5  711.85  120.81709.1997   125.2  707.01
   131.9   705.4     135  704.66   144.8  704.32   154.5  704.63   193.5  706.42
   242.3  708.48     252  709.36   261.8  712.07   271.6  717.49   291.1   730.5
   300.8  736.59   310.6  741.88   330.1  751.07   359.4  765.14   369.1  769.91
#Mann= 3 , 0 , 0
       0      .1       0  120.81    .045       0   131.9     .09       0
Bank Sta=120.81,131.9
XS Rating Curve= 0 ,0
Exp/Cntr=0.3,0.1

Type RM Length L Ch R = 1 ,1936.5  ,65,66.8,68.2
XS GIS Cut Line= 5
     1598991.789      347387.376     1599007.414      347498.487
     1599052.553      347620.015     1599095.956      347673.835
     1599061.234      347816.196
#Sta/Elev= 30
       0  723.94     9.4  723.42    18.7  722.62    65.4  717.37    74.8   716.6
    93.5  715.29   102.8   714.3   121.5  711.31   130.7  709.31   142.3  706.32
   149.2  704.55   158.5  702.82   167.8  702.26     177  702.99   186.3  704.21
   195.5  705.39   204.8  706.11   223.3  706.97   241.8  707.44   259.1  707.59
   285.1   708.2     311  708.32   320.8  708.74   330.5   710.1   340.3  713.55
   350.1  718.24   389.1  738.92   408.7  748.71     438  763.91   457.5  773.56
#Mann= 3 , 0 , 0
       0      .1       0   142.3    .045       0   186.3     .09       0
Bank Sta=142.3,186.3
XS Rating Curve= 0 ,0
Exp/Cntr=0.3,0.1

Type RM Length L Ch R = 1 ,1869.7  ,159,189.9,223.6
XS GIS Cut Line= 6
     1599019.567      347361.335     1598936.065      347383.926
     1598951.859      347503.696     1598996.998      347625.224
       1599040.4      347679.043     1599005.678      347821.404
#Sta/Elev= 30
       0  739.61    19.2  730.54    57.7   710.9    67.3   708.2    86.5  707.09
   151.6  705.96     198  704.66   207.3  703.73   225.8  701.25   227.6   701.2
   235.1  700.98   253.6  701.38   262.9  702.12   281.4  705.51   290.6   706.8
   318.4  709.63     337  710.42   371.5  710.31   388.8  710.73   397.4  711.96
   406.1  713.52   415.9  717.18   425.6  721.39   464.7   738.8   503.8  756.96
   513.6  760.89   523.3  764.41   533.1  767.45   542.9  769.84   552.6  771.68
#Mann= 3 , 0 , 0
       0     .07       0     198    .045       0   227.6     .08       0
Bank Sta=198,227.6
XS Rating Curve= 0 ,0
Exp/Cntr=0.3,0.1

Type RM Length L Ch R = 1 ,1679.8  ,244.3,261.5,278.6
XS GIS Cut Line= 4
     1599045.609      347331.821     1598934.498      347317.932
     1598769.567      347425.571     1598641.095      347495.015
#Sta/Elev= 24
       0  752.43    18.7   743.9    37.3  735.15    46.7  730.56    74.6   716.4
      84  711.84    93.3  708.74   102.6  707.69   121.4  707.16   140.1  706.53
   196.4  704.39   243.3  702.47   256.8  701.65     262  701.33   271.4  701.16
   280.8  702.24   290.2  705.86   299.5  710.78   308.9  715.27   347.9  732.07
   377.1  744.86     416  761.69   425.8  766.21     455   781.1
#Mann= 3 , 0 , 0
       0     .06       0   256.8    .045       0   280.8      .1       0
Bank Sta=256.8,280.8
XS Rating Curve= 0 ,0
Exp/Cntr=0.3,0.1

Type RM Length L Ch R = 1 ,1418.3  ,338.8,328.4,317.9
XS GIS Cut Line= 3
      1599071.65      347238.071     1598825.123      347168.626
      1598634.15      347133.904
#Sta/Elev= 30
       0   762.2    94.9  716.44   104.4  712.23   113.8  709.32   123.3  708.29
   142.3  707.93   161.3  708.03   199.2  708.73   208.7  708.76   227.7  708.38
   246.6   707.2   256.1  706.32   265.8  704.68   275.5  702.37   285.2  700.94
   294.9   701.2   304.6  702.28   324.1  704.46   333.8  705.76   343.5  709.27
   353.2  715.49   362.9  722.82   382.3  737.93     392  745.14   401.7  751.76
   411.4  757.96   421.1  763.79   430.8  769.36   440.5  774.73   450.2  779.86
#Mann= 3 , 0 , 0
       0     .06       0   275.5    .045       0   304.6      .1       0
Bank Sta=275.5,304.6
XS Rating Curve= 0 ,0
Exp/Cntr=0.3,0.1

Type RM Length L Ch R = 1 ,1089.9  ,499.1,504.2,508.2
XS GIS Cut Line= 4
     1599089.691      346808.287     1598919.982      346803.115
     1598747.128       346853.88     1598619.325      346954.258
#Sta/Elev= 30
       0  745.55    37.7  728.58      66  716.14    75.5  712.13    84.9  708.76
    94.3     707   103.8  706.42   188.8  702.39   245.6  699.58   274.1  698.06
   283.6  697.65     293  697.62   301.2  698.17   302.5  698.26     312  699.58
   321.5  701.09   349.9  704.71   359.5   706.7   369.1     710   378.6  714.21
   388.2  718.91   397.7  723.85   407.3     729   426.4  739.63   445.5   749.9
   455.1  754.72   464.6  759.05   474.2  762.48   502.9  770.64   512.4  773.63
#Mann= 3 , 0 , 0
       0     .08       0   274.1    .045       0   301.2     .08       0
Bank Sta=274.1,301.2
XS Rating Curve= 0 ,0
Exp/Cntr=0.3,0.1

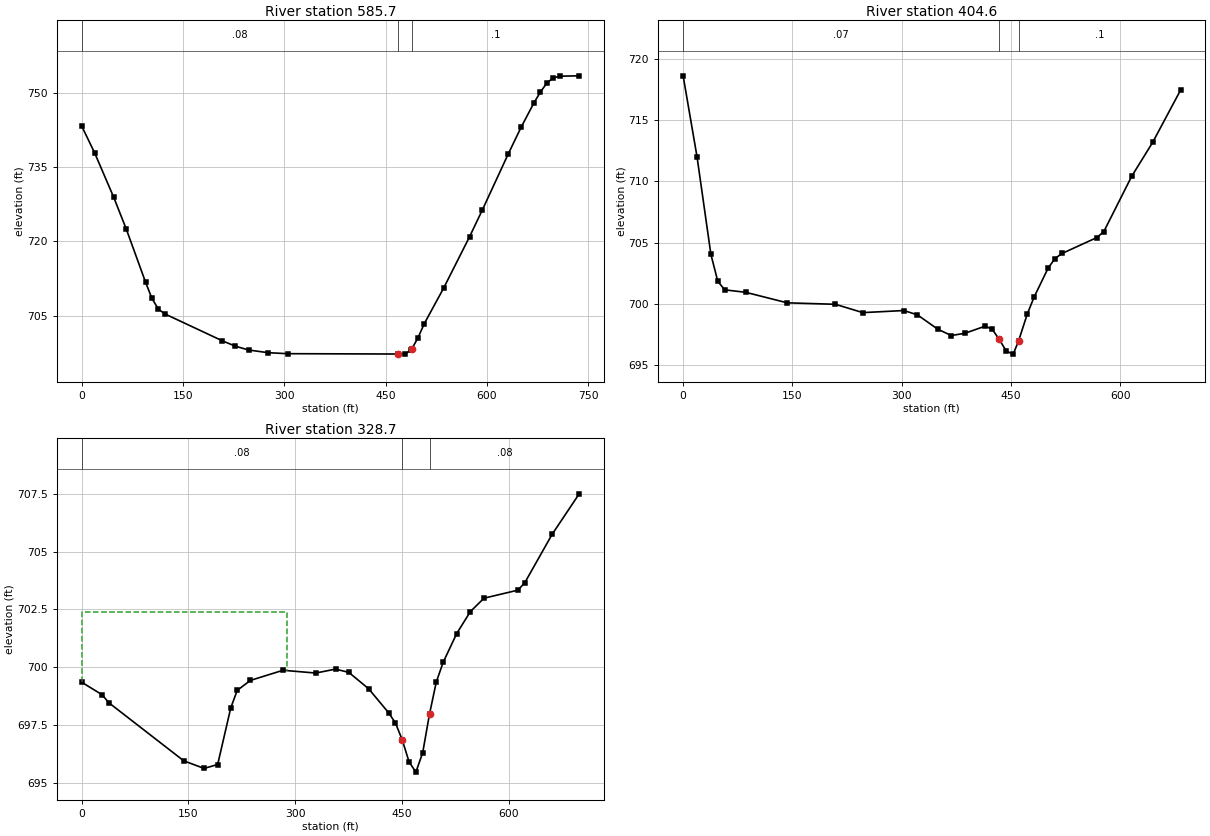
Type RM Length L Ch R = 1 ,585.7   ,187.3,181.1,174.5
XS GIS Cut Line= 4
     1599024.775      346468.974     1598845.956      346453.349
     1598521.303      346500.224      1598321.65      346613.071
#Sta/Elev= 30
       0   743.3    18.9  737.96    47.2  728.97    66.1  722.44    94.5  711.76
   103.9  708.49   113.4  706.33   122.8  705.37   208.4   699.9   227.7  698.82
     247  698.06     276  697.51   304.9  697.31   468.9  697.24   478.6  697.22
   488.2   698.1   489.1  698.32   497.9  700.48   507.5  703.41   536.2  710.61
   574.4  720.94   593.5   726.4   631.7  737.68   650.9  743.11     670  748.07
   679.5  750.23   689.1  752.07   698.6  753.09   708.2  753.43   736.9   753.5
#Mann= 3 , 0 , 0
       0     .08       0   468.9    .045       0   489.1      .1       0
Bank Sta=468.9,489.1
XS Rating Curve= 0 ,0
Exp/Cntr=0.3,0.1

Type RM Length L Ch R = 1 ,404.6   ,75.8,76,76.1
XS GIS Cut Line= 5
     1598948.387      346378.696     1598802.553      346288.418
     1598672.345      346271.057     1598573.387      346297.099
     1598319.914      346409.946
#Sta/Elev= 30
       0  718.62    19.1     712    38.1  704.04    47.6  701.83    57.2  701.14
    85.8  700.94   142.9  700.08     209  699.96   246.6  699.28   302.9  699.45
   321.5   699.1   349.4  697.93     368  697.41   386.6  697.59   414.8  698.18
   424.3  697.91   433.9  697.09   443.5  696.14     453  695.89   460.3  696.95
   472.2  699.14   481.7  700.55   500.9  702.91   510.4   703.7     520  704.11
   567.8  705.41   577.4   705.9   615.7  710.42   644.4  713.18   682.7  717.45
#Mann= 3 , 0 , 0
       0     .07       0   433.9    .045       0   460.3      .1       0
Bank Sta=433.9,460.3
XS Rating Curve= 0 ,0
Exp/Cntr=0.3,0.1

Type RM Length L Ch R = 1 ,328.7   ,300.4,328.7,356.8
XS GIS Cut Line= 5
     1598958.803      346300.571     1598786.928      346217.237
     1598660.192      346196.404     1598561.234      346222.446
     1598307.762      346335.293
#Sta/Elev= 30
       0  699.34    28.6   698.8    38.2  698.45   143.3  695.94   171.9  695.61
     191  695.78   209.4  698.23   218.5  698.99   236.9  699.42   282.8  699.86
   328.8  699.74   356.7  699.91   375.3  699.77   403.2  699.06   431.3  698.02
   440.9  697.58   450.5  696.84     460   695.9   469.6  695.45   479.2  696.29
   488.8  697.97   498.3  699.35   507.9   700.2     527  701.45   546.2   702.4
   565.3  702.98   613.1  703.33   622.7  703.65     661  705.74   699.2   707.5
#Mann= 3 , 0 , 0
       0     .08       0   450.5    .045       0   488.8     .08       0
#XS Ineff= 2 , 0
          288.93  702.39
Permanent Ineff=
       F       F
Bank Sta=450.5,488.8
XS Rating Curve= 0 ,0
Exp/Cntr=0.3,0.1

Chan Stop Cuts=-1
Use User Specified Reach Order=0
Composite Channel Slope=5